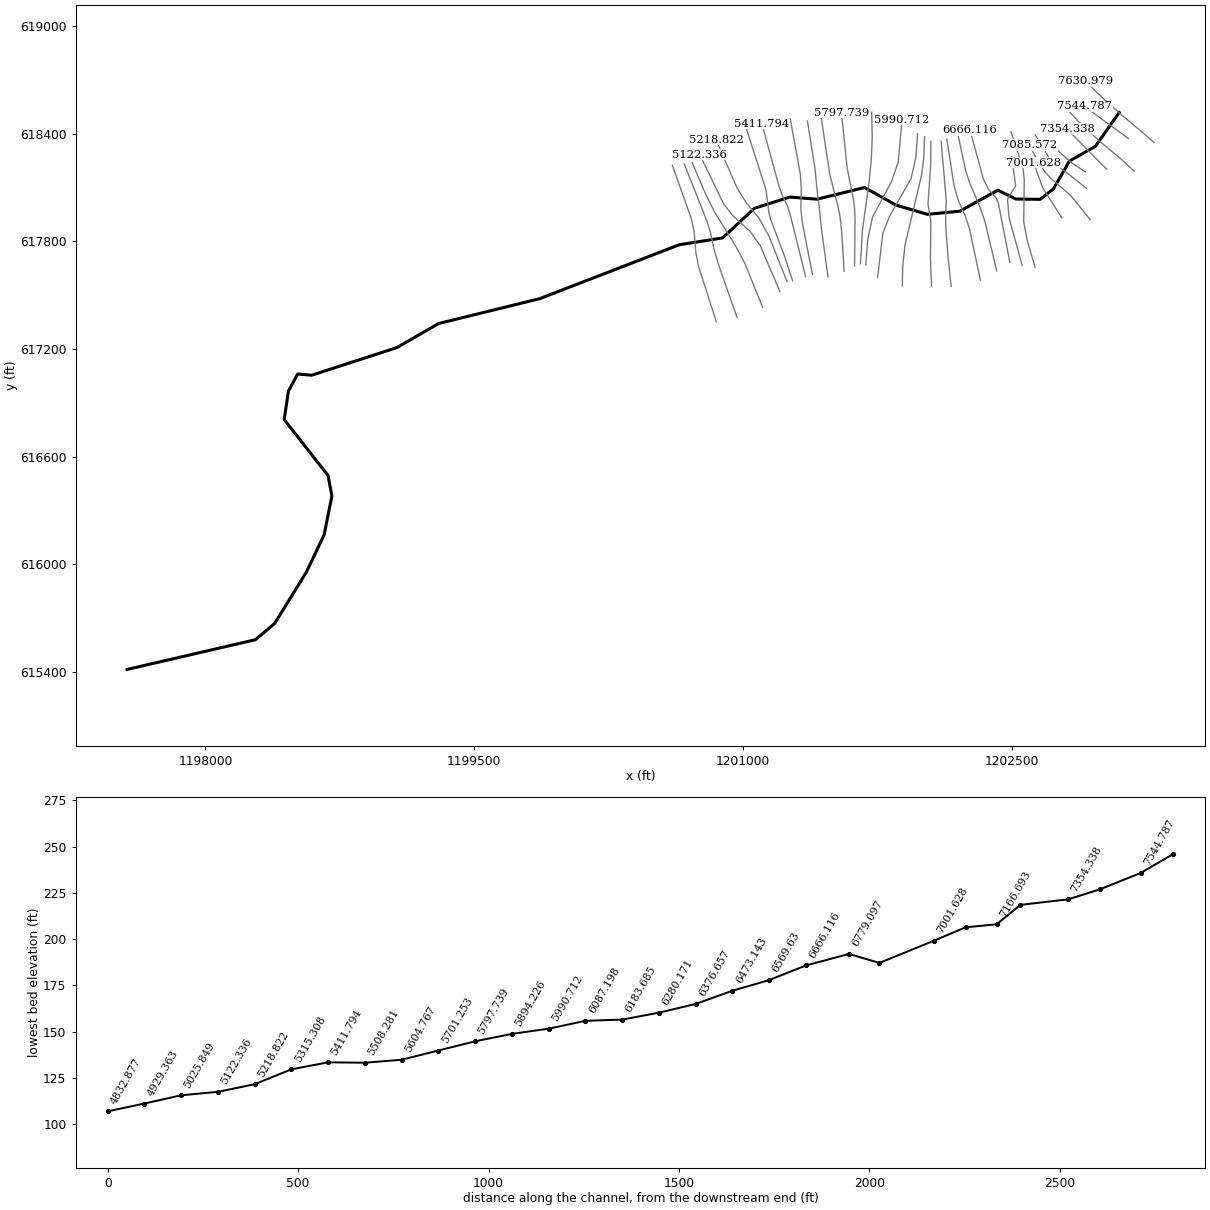
--- 148_ras.prj (project) ---

Proj Title=148
Current Plan=p01
Default Exp/Contr=0.3,0.1
English Units
Geom File=g01
Flow File=f01
Plan File=p01
Y Axis Title=Elevation
X Axis Title(PF)=Main Channel Distance
X Axis Title(XS)=Station
BEGIN DESCRIPTION:
RFD model 148 exported to HEC-RAS
END DESCRIPTION:

--- 148_ras.p01 (plan) ---

Plan Title=Plan 01
Program Version=4.10
Short Identifier=Plan 01
Geom File=g01
Flow File=f01
Subcritical Flow
Calc Critical at every XS
Secant Critical Depth

--- 148_ras.f01 (steady flow) ---

Flow Title=Flow 01
Program Version=5.01
Number of Profiles= 5
Profile Names=10yr,25yr,50yr,100yr,500yr
River Rch & RM=148,49,7630.979
  457.94  560.55   672.2  735.95  892.38
River Rch & RM=148,49,7438.006
  461.29  565.26  678.01  743.11  902.31
River Rch & RM=148,49,7354.338
  468.54  575.46   690.6  758.65  923.91
River Rch & RM=148,49,7229.365
  474.99  584.54  701.81  772.54  943.26
River Rch & RM=148,49,7166.693
  480.68  592.57  711.74  784.84  960.45
River Rch & RM=148,49,7001.628
  661.77  854.84  1037.7  1199.7 1559.95
River Rch & RM=148,49,6859.089
  664.06  858.24 1041.95 1205.23 1568.16
River Rch & RM=148,49,6779.097
  667.11  862.75 1047.58 1212.56 1579.07
River Rch & RM=148,49, 6569.63
  677.59  878.31 1067.02 1237.92 1616.87
River Rch & RM=148,49,6473.143
  690.35   897.3 1090.77 1268.97  1663.3
River Rch & RM=148,49,6183.685
  716.55  936.43 1139.75 1333.28    1760
River Rch & RM=148,49,6087.198
  718.93  939.99  1144.2 1339.14 1768.84
River Rch & RM=148,49,5894.226
  719.94   941.5 1146.11 1341.65 1772.62
River Rch & RM=148,49,5797.739
  727.96  953.54 1161.18 1361.53 1802.67
River Rch & RM=148,49,5701.253
  733.24  961.46 1171.11 1374.64 1822.53
River Rch & RM=148,49,5604.767
  741.04   973.2 1185.83 1394.09 1852.03
River Rch & RM=148,49,5508.281
  741.69  974.17 1187.04  1395.7 1854.48
River Rch & RM=148,49,5411.794
  749.36  985.73 1201.53 1414.89 1883.65
River Rch & RM=148,49,5315.308
  751.57  989.07 1205.72 1420.44  1892.1
River Rch & RM=148,49,5122.336
  753.78  992.39 1209.89 1425.98 1900.53
River Rch & RM=148,49,5025.849
  758.47  999.48 1218.78 1437.77  1918.5
River Rch & RM=148,49,4929.363
  763.11  1006.5 1227.59 1449.47 1936.36
River Rch & RM=148,49,4832.877
  765.57 1010.22 1232.26 1455.68 1945.84
River Rch & RM=148,49, 4736.39
  771.67 1019.45 1243.85 1471.09  1969.4
River Rch & RM=148,49,4639.904
  773.19 1021.74 1246.73 1474.92 1975.27
River Rch & RM=148,49,4543.418
  791.88  1050.1 1282.35 1522.44 2048.16
River Rch & RM=148,49,4350.445
  794.21 1053.64 1286.79 1528.37 2057.29
River Rch & RM=148,49,4157.473
  801.98 1065.47 1301.66 1548.26 2087.91
River Rch & RM=148,49,  3964.5
   805.4 1070.67  1308.2 1557.02 2101.43
River Rch & RM=148,49,3771.528
  807.66 1074.13 1312.55 1562.84  2110.4
River Rch & RM=148,49,3578.555
  814.96 1085.26 1326.55 1581.62  2139.4
River Rch & RM=148,49,3385.582
  820.23 1093.31 1336.67 1595.21 2160.43
River Rch & RM=148,49, 3192.61
  821.61 1095.41 1339.32 1598.77 2165.94
River Rch & RM=148,49,2999.637
  822.71  1097.1 1341.44 1601.61 2170.34
River Rch & RM=148,49,2806.665
  824.63 1100.03 1345.13 1606.57 2178.03
River Rch & RM=148,49,  2533.1
  830.08 1108.37 1355.62 1620.68  2199.9
Boundary for River Rch & Prof#=148,49,1
Up Type= 0
Dn Type= 2
Boundary for River Rch & Prof#=148,49,2
Up Type= 0
Dn Type= 2
Boundary for River Rch & Prof#=148,49,2
Up Type= 0
Dn Type= 2
Boundary for River Rch & Prof#=148,49,2
Up Type= 0
Dn Type= 2
Boundary for River Rch & Prof#=148,49,2
Up Type= 0
Dn Type= 2

--- 148_ras.g01 (geometry) ---

Geom Title=148
Program Version=4.10

River Reach=148,49
Reach XY= 30
1203098.94464436618518.4419571911202966.44467807618330.108683586
1202821.44471845618247.6087122861202732.44866773618092.698720932
1202658.25653273618034.2921465341202522.50071123618035.870702624
1202421.95108768618085.317466825 1202209.9466106617967.992791861
1202029.20194128617950.6286751631201853.98221815618001.931747258
1201678.11171821618100.1087890421201413.94512761618035.108815968
1201261.44517297618046.7754835491201063.11189634617984.275507808
1200886.44527704617819.2755619141200643.94534749617780.942246959
1199864.77890211617480.1090254191199301.44573092  617341.7757494
1199068.94579569617207.6091292051198593.11259836617053.442522049
1198514.77928832617060.1091889891198463.11263415616964.275885612
1198439.77930307616805.9425999671198684.77922183616493.442685679
1198705.61254567616379.2760523111198662.27921891616162.609451219
 1198563.1125755615955.1095156671198386.44595271615669.276272297
 1198278.9459818615578.4429690241197562.56567666 615412.62692222

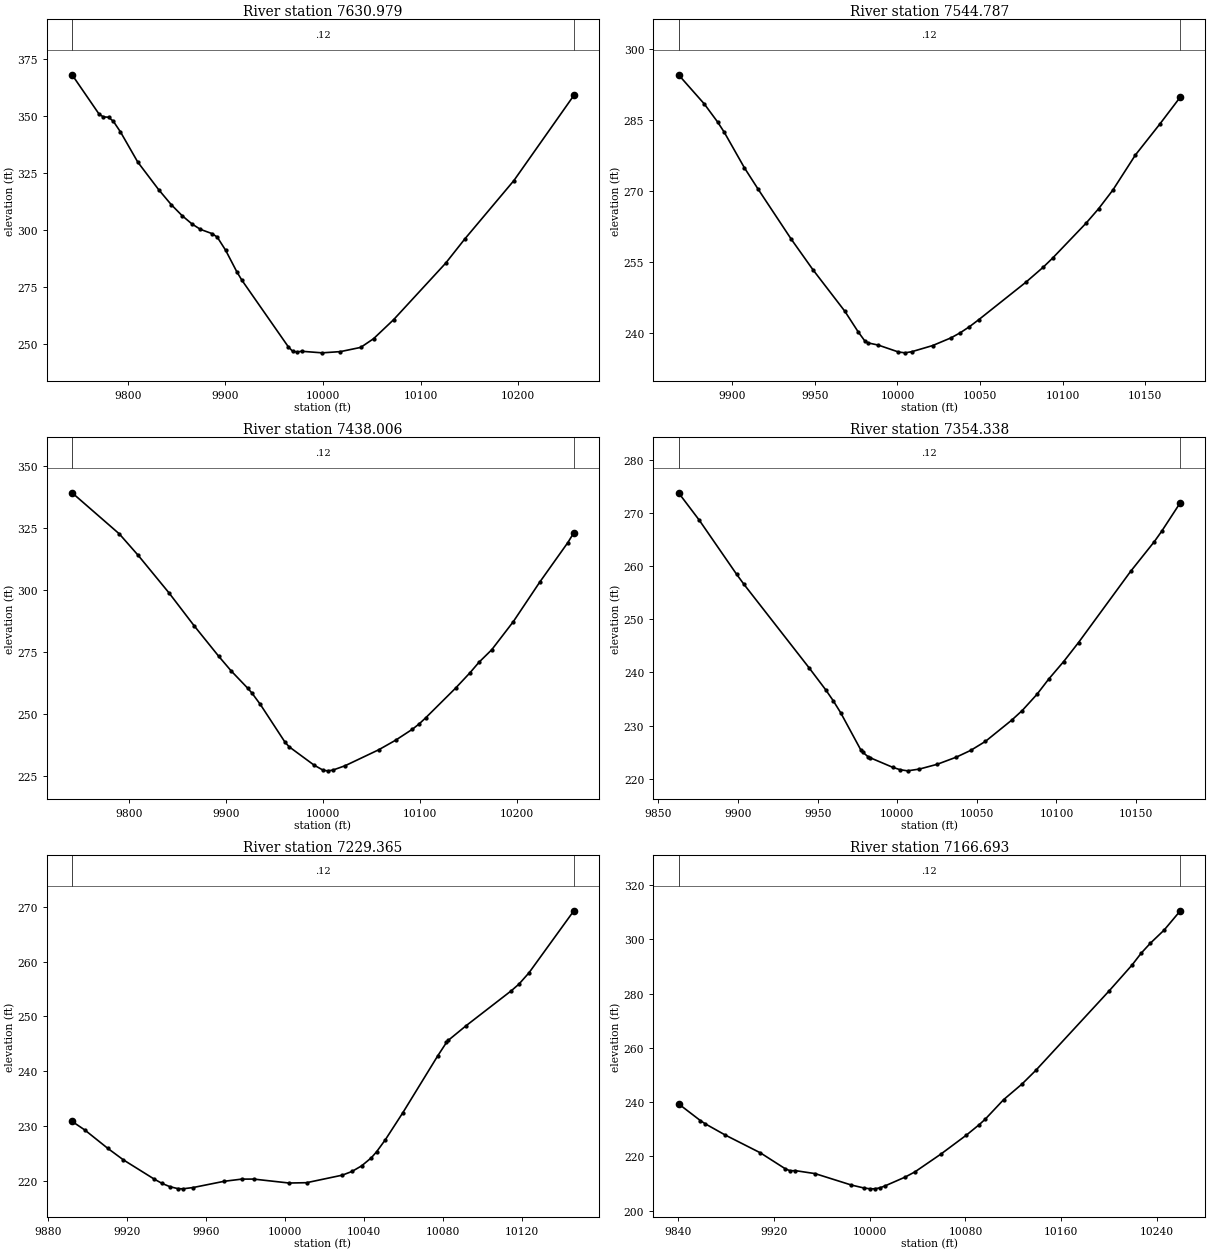
Type RM Length L Ch R = 1 ,7630.979,86.192100,86.192100,86.192100
XS GIS Cut Line= 6
1203293.62873834618350.790817142  1203227.804443618408.350845017
1203118.03776243618500.530910608 1203038.4434836618570.743547997
1202972.25696667618632.1849392961202911.55041872618694.014325333
#Sta/Elev= 30
9743.057368.2759 9770.74350.97459775.098349.77569780.411349.62979785.395347.8001
9792.531343.23759810.315329.92949831.734317.79429844.587 311.2239855.754306.3697
9866.008302.66699874.577300.33469886.364298.48169891.714296.94949900.282291.1935
9911.872281.62379916.973278.00059964.546248.71219968.831246.82299973.091246.4662
9978.109246.76639999.177246.083210017.93246.625510038.63248.473810051.78252.2839
10072.32260.649210125.56285.4467 10145.2296.104910195.56321.816110256.93359.2122
#Mann= 3 , 0 , 0
9743.057    0.12       09743.057    0.12       010256.93    0.12       0
#XS Ineff= 2 , 0
       0                               0
Bank Sta=9743.057,10256.93
Exp/Cntr=0.3,0.1

Type RM Length L Ch R = 1 ,7544.787,106.780400,106.780400,106.780400
XS GIS Cut Line= 2
1203150.82416597618373.5349744561202905.07803094618552.129549325
#Sta/Elev= 30
9867.459 294.4939882.972288.36949891.083284.54039895.139282.35479907.306274.8648
9915.417270.45389935.696259.76919948.727253.36329968.142244.54699976.253240.1736
9980.309238.24219982.211237.8608 9988.42237.392910000.59235.941510004.64235.7602
 10008.7236.005710021.28237.295810032.44238.929110038.02240.0012 10043.6241.2854
10049.26242.776210077.65250.647810088.24253.847510093.87255.749110114.15263.1359
10121.73266.183610130.37270.127110144.05277.549310158.76284.048410171.25289.7917
#Mann= 3 , 0 , 0
9867.459    0.12       09867.459    0.12       010171.25    0.12       0
#XS Ineff= 2 , 0
       0                               0
Bank Sta=9867.459,10171.25
Exp/Cntr=0.3,0.1

Type RM Length L Ch R = 1 ,7438.006,83.668100,83.668100,83.668100
XS GIS Cut Line= 6
1203182.58942188618191.5288593821203107.14544048618260.567464407
1202999.69751815618350.5228988721202915.29497451 618425.86969167
1202862.65634891618477.4810334621202802.75005496618542.948452699
#Sta/Elev= 30
9740.984339.07399789.767322.48919809.206313.85859841.077 298.6899866.833285.5238
9892.505273.07049905.342267.18739922.457260.19529926.736258.27139935.294253.7407
9960.967238.39199965.245236.5842 9990.96229.194310000.33227.1543 10004.9226.9271
10009.96227.1951 10022.8 228.97810057.58235.429610074.97239.275210092.36243.7158
10099.41245.8946 10105.9 248.252 10136.9260.281110151.85 266.51410161.04270.7108
10174.18275.750510196.42287.058110223.68302.980710252.84319.016910259.01322.9597
#Mann= 3 , 0 , 0
9740.984    0.12       09740.984    0.12       010259.01    0.12       0
#XS Ineff= 2 , 0
       0                               0
Bank Sta=9740.984,10259.01
Exp/Cntr=0.3,0.1

Type RM Length L Ch R = 1 ,7354.338,124.972700,124.972700,124.972700
XS GIS Cut Line= 2
1203029.37985504618202.0841826351202807.92258224618426.398968622
#Sta/Elev= 30
9862.611273.77269875.616268.63329899.076258.46479903.746256.55629944.771240.8204
9955.114236.72599959.784234.69619964.454 232.4459977.043225.48879978.463224.9855
9981.654224.17639983.133 223.9639997.143222.184610001.81221.730210006.48221.5192
10013.93 221.85210025.16222.755310036.98224.0783 10046.2225.371310055.42227.0596
10071.86231.034110078.47232.838410087.69235.867610095.21238.783610104.55242.0574
10113.89245.636410146.58258.994910161.46264.578710166.07266.520210177.83271.9184
#Mann= 3 , 0 , 0
9862.611    0.12       09862.611    0.12       010177.83    0.12       0
#XS Ineff= 2 , 0
       0                               0
Bank Sta=9862.611,10177.83
Exp/Cntr=0.3,0.1

Type RM Length L Ch R = 1 ,7229.365,62.672300,62.672300,62.672300
XS GIS Cut Line= 4
1202910.66052562618187.098400712  1202829.305444618240.576566264
1202755.91519555618307.1398148831202726.33152953618356.635563836
#Sta/Elev= 30
9892.113230.83649898.485 229.2919910.264225.90129918.116223.81469933.821220.2873
9937.747219.51479941.673218.92559945.599218.58099948.189218.53479953.452218.7772
9969.156219.91299978.053220.30919984.025220.315310001.99219.596110010.85 219.654
10028.97221.032510033.85221.706310038.74222.727510043.62224.189810046.28225.2794
10050.71227.470910059.57232.399210077.28242.795410081.71245.238110082.69245.6471
10091.61248.282810114.54254.671310118.36255.863110123.44257.918310146.21269.2553
#Mann= 3 , 0 , 0
9892.113    0.12       09892.113    0.12       010146.21    0.12       0
#XS Ineff= 2 , 0
       0                               0
Bank Sta=9892.113,10146.21
Exp/Cntr=0.3,0.1

Type RM Length L Ch R = 1 ,7166.693,81.121500,81.121500,81.121500
XS GIS Cut Line= 3
1202916.50808376618096.3561943021202715.05340332618253.519420162
1202630.75676399618393.537566856
#Sta/Elev= 30
9840.468239.36099858.799233.1571 9862.96231.94569879.604227.82549908.732  221.31
9929.538215.43379933.699214.6671 9937.86214.74099954.505213.6324 9984.73209.4265
9995.398 208.31710000.73208.020110004.44208.0503 10008.6208.396310012.76 209.082
10029.41212.301310037.73 214.245 10059.4220.797610080.74227.808510091.41231.6508
10096.52233.700410111.84240.884210127.16246.634810138.65251.654910199.92280.9748
10219.07290.514510226.73294.902710234.39298.576310245.88303.422410259.41310.5363
#Mann= 3 , 0 , 0
9840.468    0.12       09840.468    0.12       010259.41    0.12       0
#XS Ineff= 2 , 0
       0                               0
Bank Sta=9840.468,10259.41
Exp/Cntr=0.3,0.1

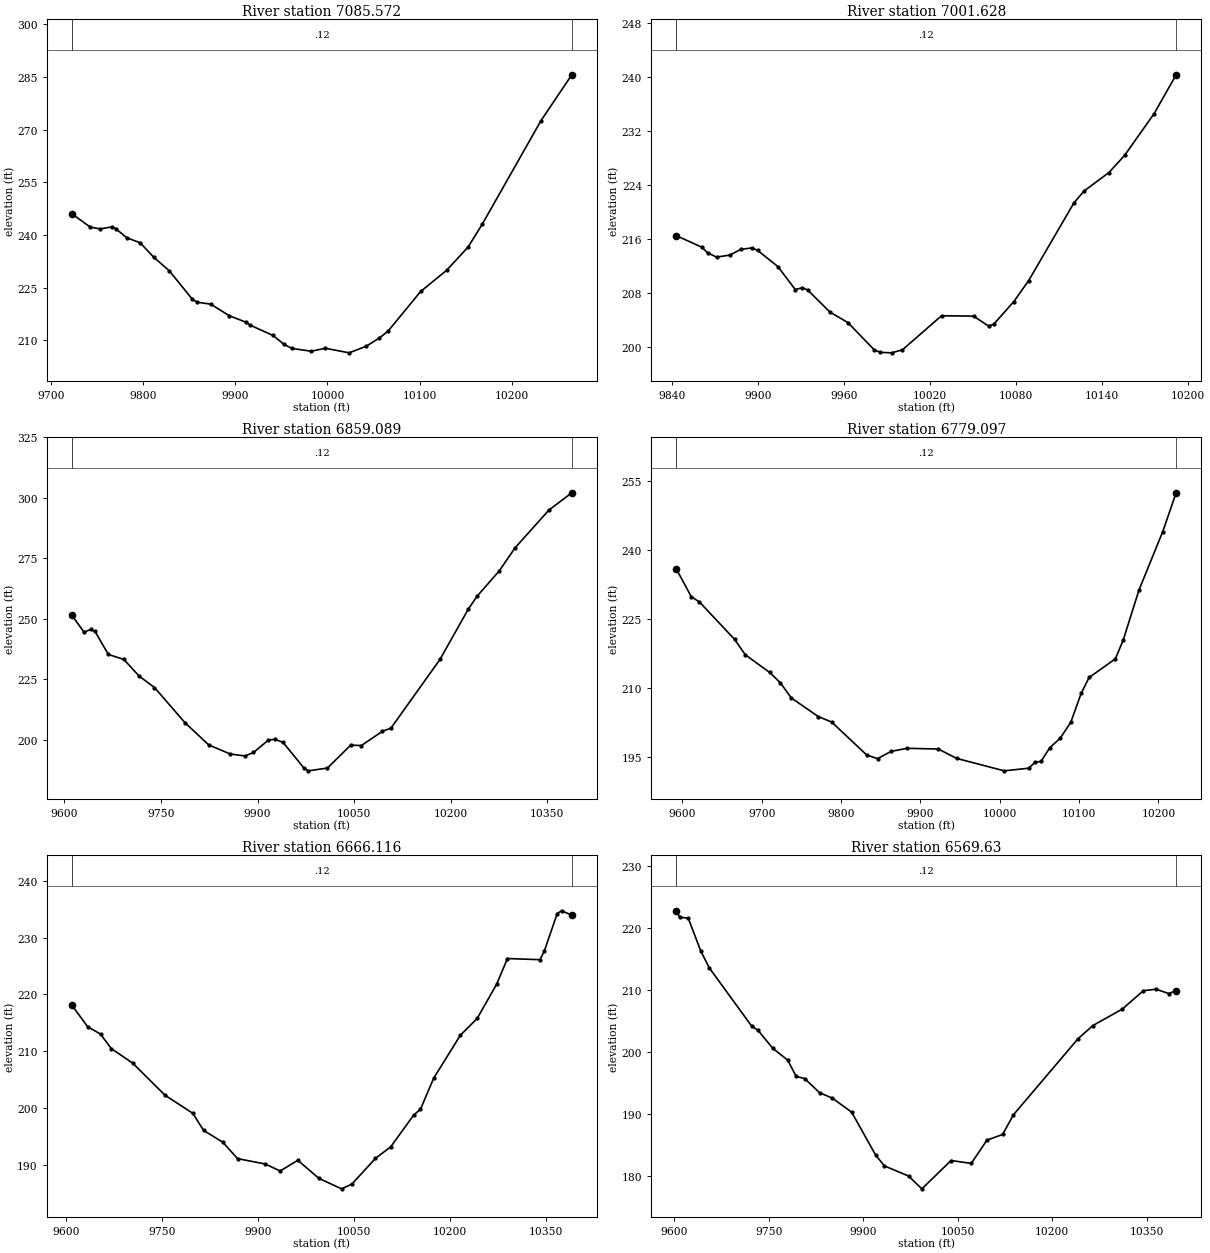
Type RM Length L Ch R = 1 ,7085.572,83.944100,83.944100,83.944100
XS GIS Cut Line= 6
1202937.14235476617921.1859997491202829.93921456618053.697491236
1202719.98679646618149.5958848111202684.82489866618186.449106262
1202643.68763241618247.529577121 1202598.3004317618337.581006201
#Sta/Elev= 30
9722.914245.98039742.869242.20919753.637241.71479766.028242.27069770.158 241.818
9782.549239.16169796.878237.7563 9811.46233.68149828.656229.71739853.612221.6245
9858.603220.84229873.577220.25899893.679216.95089911.787215.11589916.351214.2634
9940.879211.37389952.859208.81339961.583207.65539982.521206.85619997.581207.7168
10023.53206.403510041.95208.273610056.21210.601610065.72212.584610101.08223.8796
10129.33229.934810152.49236.526610167.76 242.98810231.62 272.55610265.04285.6164
#Mann= 3 , 0 , 0
9722.914    0.12       09722.914    0.12       010265.04    0.12       0
#XS Ineff= 2 , 0
       0                               0
Bank Sta=9722.914,10265.04
Exp/Cntr=0.3,0.1

Type RM Length L Ch R = 1 ,7001.628,142.539000,142.539000,142.539000
XS GIS Cut Line= 3
1202779.34745026 617930.620428831202672.85336399618097.778485924
1202620.51303172618238.869816303
#Sta/Elev= 30
9842.859216.4841 9860.61214.77689864.833213.91519870.939213.30689880.061213.5897
9887.841 214.4469895.363214.66079899.511214.31379913.681211.90539925.893208.4778
9930.632208.75969934.522208.42779950.082205.14319962.529203.59479980.847199.5755
9985.093199.17459993.059199.103310000.65199.557410027.88204.6045 10050.2204.5475
 10060.7203.0803 10064.2203.3282 10078.2206.6765 10088.7209.828710120.19221.3233
10127.27223.095510144.68225.846810155.57228.380710176.18234.578910191.55 240.341
#Mann= 3 , 0 , 0
9842.859    0.12       09842.859    0.12       010191.55    0.12       0
#XS Ineff= 2 , 0
       0                               0
Bank Sta=9842.859,10191.55
Exp/Cntr=0.3,0.1

Type RM Length L Ch R = 1 ,6859.089,79.991500,79.991500,79.991500
XS GIS Cut Line= 6
1202629.47757794617655.3866568061202585.85990405617804.767697691
1202566.27971801617909.1297688361202569.32831764618141.237660467
1202563.10022493618205.0232382221202495.28840827 618411.93380083
#Sta/Elev= 30
9611.699251.38499630.438244.45999640.745245.57399647.616 244.741 9668.23235.2425
9692.279233.19889716.126226.28579739.907221.57479787.239207.05589824.145197.8628
9857.352194.12679880.531193.28129893.692194.73099916.722199.82649926.588200.1972
9939.711198.9024 9972.52188.14639979.082 187.14610008.63188.304110044.79197.7874
10061.23197.591410094.11   203.510107.27204.787510183.41233.184810227.45253.9925
10241.11 259.32610275.66269.829710299.97279.273910352.65294.914510388.26302.0669
#Mann= 3 , 0 , 0
9611.699    0.12       09611.699    0.12       010388.26    0.12       0
#XS Ineff= 2 , 0
       09929.548                       0
Bank Sta=9611.699,10388.26
Exp/Cntr=0.3,0.1

Type RM Length L Ch R = 1 ,6779.097,112.981100,112.981100,112.981100
XS GIS Cut Line= 6
1202557.89017746617664.8717014641202483.88767323617933.501817405
1202475.93042895618031.0998710241202481.57217675618045.909459054
1202521.06441146618109.3791220341202499.90785715618270.874153331
#Sta/Elev= 30
9592.351235.84919611.284  229.829621.493228.69169665.732220.56719679.345217.2057
9709.972213.38559723.584211.11299737.197207.85269771.227203.79289788.242202.5867
9832.482195.41779846.094194.64729863.109196.22029883.117196.88959922.618 196.736
 9945.66194.695410005.71191.994310036.62192.568810044.35 193.83710052.08 194.033
10063.08197.013310076.31199.092310089.55202.526110102.78208.874610112.71212.2799
 10145.8216.330110155.72220.426110175.58231.283310205.36 243.91210222.39252.4049
#Mann= 3 , 0 , 0
9592.351    0.12       09592.351    0.12       010222.39    0.12       0
#XS Ineff= 2 , 0
       09933.219                       0
Bank Sta=9592.351,10222.39
Exp/Cntr=0.3,0.1

Type RM Length L Ch R = 1 ,6666.116,96.486300,96.486300,96.486300
XS GIS Cut Line= 6
1202489.19190838 617682.292977131202424.17598815618016.098501568
1202411.88152278618041.3902117861202368.49765829 618091.40652159
1202340.83247264 618148.496517151202266.73084863618420.494678145
#Sta/Elev= 30
 9609.79218.08139634.176214.32559654.347213.01149671.157210.46769704.777207.8855
9755.204202.24169798.548 199.0649815.218196.06879845.102193.99379868.331191.0953
9911.471190.14899934.913188.92169962.433190.80159995.277187.627210030.63185.7744
 10046.7186.593110083.67191.133710107.63193.187310143.45198.778110153.88199.7727
10174.46205.226710216.11212.790710242.44215.759410272.85221.787910289.74226.3124
10340.41226.107710347.17227.575510367.43234.231610374.19234.717810390.24 233.953
#Mann= 3 , 0 , 0
 9609.79    0.12       0 9609.79    0.12       010390.24    0.12       0
#XS Ineff= 2 , 0
       09945.071                       0
Bank Sta=9609.79,10390.24
Exp/Cntr=0.3,0.1

Type RM Length L Ch R = 1 , 6569.63,96.486300,96.486300,96.486300
XS GIS Cut Line= 6
1202415.53073947617635.1456037211202349.62344341617912.166923128
1202318.16048447618000.880089935 1202265.2239008618124.841537887
1202242.98358677618191.8178296921202198.67408299618396.931872674
#Sta/Elev= 30
9602.892222.72729608.353221.67889621.805221.54529641.982216.18429655.434213.4984
9722.692204.1196 9732.78203.43959756.321200.52719779.861198.64289793.313196.0212
9806.874195.65519830.631193.37499850.994192.50189881.538190.23569919.672 183.309
9933.596181.57189971.888179.94279993.069177.874210039.47182.441810071.56181.9779
10096.52 185.73410121.33186.641810138.61 189.821 10241.1202.079110264.76204.2123
10311.65206.877610345.07209.838110365.12210.073710385.17209.3815 10397.1209.8196
#Mann= 3 , 0 , 0
9602.892    0.12       09602.892    0.12       0 10397.1    0.12       0
#XS Ineff= 2 , 0
       0                               0
Bank Sta=9602.892,10397.1
Exp/Cntr=0.3,0.1

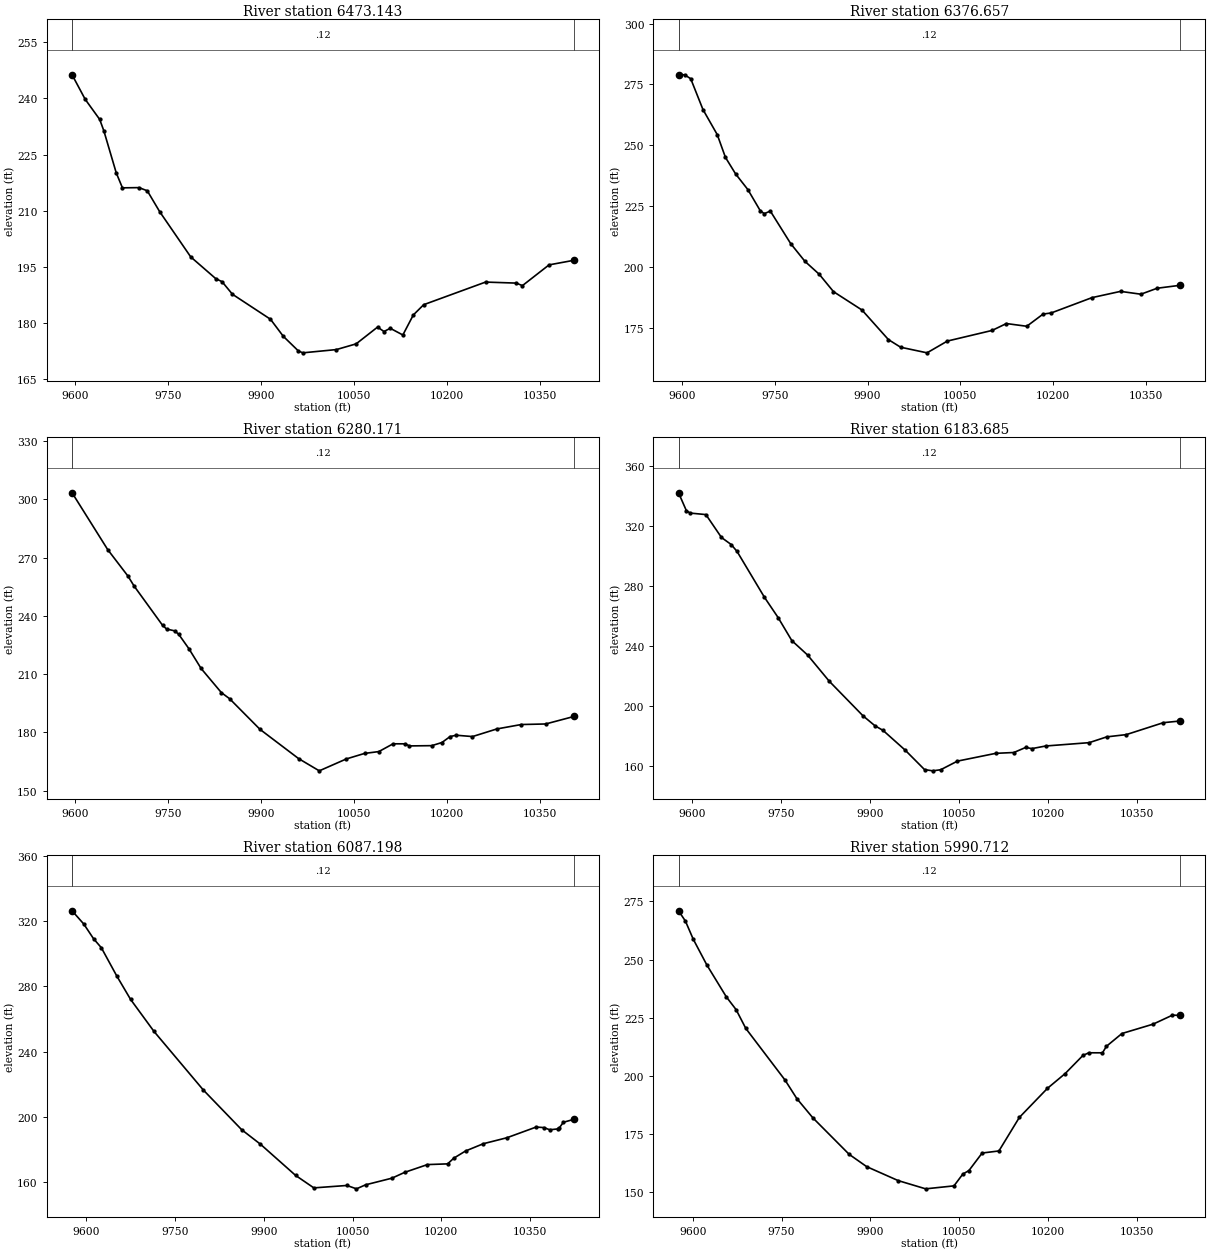
Type RM Length L Ch R = 1 ,6473.143,96.486200,96.486200,96.486200
XS GIS Cut Line= 6
1202324.32772753617583.5634312331202263.71856972617870.659257171
1202241.31650818617937.6248682211202200.16696726618030.524154145
  1202177.872576618107.9094683481202137.28440237618369.205474938
#Sta/Elev= 30
9594.585246.30749615.805239.7543 9639.21234.39629645.898231.3748 9665.96220.1297
9675.991216.1292 9702.74216.19119716.115215.34839736.177209.76489786.331197.6986
9826.784 191.8989836.907191.08959853.779187.72359915.186181.05959935.943176.5015
9960.221172.60939967.426172.093210021.72172.963310053.65 174.48910088.28178.9707
10098.59177.783610108.76178.642810129.11176.858110146.01 182.19910162.78184.9414
10262.78  190.9810312.41190.705310322.34190.032410365.35195.570310405.45196.7927
#Mann= 3 , 0 , 0
9594.585    0.12       09594.585    0.12       010405.45    0.12       0
#XS Ineff= 2 , 0
       0                               0
Bank Sta=9594.585,10405.45
Exp/Cntr=0.3,0.1

Type RM Length L Ch R = 1 ,6376.657,96.486300,96.486300,96.486300
XS GIS Cut Line= 6
 1202161.5633872617548.716493971 1202147.4736284617677.587958664
1202133.70515729617841.7963635471202130.77203266617907.916520035
1202133.76554764618032.623391659 1202105.5767509618356.892788006
#Sta/Elev= 30
9594.541278.93949604.335278.97619614.237277.35479634.039264.70749657.142254.4145
9670.343245.10129686.845238.29069706.647231.86419726.444223.29599733.029222.0189
9742.906223.07239775.829209.72259798.876202.44529821.922197.16289844.969 190.031
9891.056182.49039933.749170.36149953.453167.24279996.119164.940510028.98169.7707
10101.28174.130510124.35176.9524 10157.3175.837810183.66180.833210196.84181.3009
10262.73187.583210308.81190.145410341.72188.984210368.05191.436910405.46192.6513
#Mann= 3 , 0 , 0
9594.541    0.12       09594.541    0.12       010405.46    0.12       0
#XS Ineff= 2 , 0
       0                               0
Bank Sta=9594.541,10405.46
Exp/Cntr=0.3,0.1

Type RM Length L Ch R = 1 ,6280.171,96.486300,96.486300,96.486300
XS GIS Cut Line= 6
1202051.96932743617550.2241560141202045.82163075617705.869170594
1202047.88261499 617910.218141921202032.13960683618008.656892516
1202046.96170546 618225.973142271202048.31462007 618358.61030471
#Sta/Elev= 30
9594.592303.31799652.122274.09999684.963260.42079694.809255.32749740.754235.1445
9747.317 233.1989760.442232.26369767.004230.45029783.409223.06399803.095212.9031
9835.905200.45859849.029197.37659898.244181.5764 9960.62166.53349994.018160.2323
 10037.7166.350610067.27 169.20210090.25170.139310113.27 174.14210133.01174.1293
10139.59173.059410175.79 173.19210192.24174.8093 10205.4177.873710215.27178.5581
10241.59 177.87110281.05181.797410320.44184.064510359.82184.348710405.38188.2026
#Mann= 3 , 0 , 0
9594.592    0.12       09594.592    0.12       010405.38    0.12       0
#XS Ineff= 2 , 0
       0                               0
Bank Sta=9594.592,10405.38
Exp/Cntr=0.3,0.1

Type RM Length L Ch R = 1 ,6183.685,96.486300,96.486300,96.486300
XS GIS Cut Line= 6
1201888.97729769 617551.742152891201891.12539406617658.906835587
1201903.41100421617777.2852947711201995.93762828618168.424742378
1202008.11178217618259.0332637751202013.09939218618384.287377396
#Sta/Elev= 30
9577.409342.15299590.683330.14589597.246328.59069623.498327.5876 9649.75312.2956
9666.158307.58239676.002302.96219722.049272.41229745.113258.8415 9768.26243.4286
9794.713 233.8429831.279216.32469888.173193.20759908.326186.56579921.861183.5028
9959.082170.34119991.779157.313410005.62156.492510018.97 157.22310047.18 162.983
 10111.8168.182410142.23168.733410162.38172.158610172.45171.320810195.96173.0862
10269.02175.306910298.73179.175610331.61180.6823   10394188.6533 10422.6189.7827
#Mann= 3 , 0 , 0
9577.409    0.12       09577.409    0.12       0 10422.6    0.12       0
#XS Ineff= 2 , 0
       0                               0
Bank Sta=9577.409,10422.6
Exp/Cntr=0.3,0.1

Type RM Length L Ch R = 1 ,6087.198,96.486300,96.486300,96.486300
XS GIS Cut Line= 6
1201750.82768828617597.5960386131201780.32033979617844.046559412
1201816.25388469617937.5836674751201937.99615074618150.749294998
  1201964.697035618268.901166833 1201973.8455917618399.690436208
#Sta/Elev= 30
9575.953326.3238 9595.88 318.1379612.297309.1732 9625.43 303.6739651.697286.2207
9674.745272.04799714.311252.40439797.704216.47359862.629192.08529894.306 183.206
9953.788164.06179984.596156.420410040.54157.899810056.67155.833710071.98158.2947
10116.55162.3681 10138.2 165.95610176.65170.710110210.73171.141310220.96174.5899
10241.04179.044910271.07183.4993 10310.9187.156710360.34193.718710373.47193.3924
10383.33192.050510396.46192.556910399.74193.319610406.31196.641710424.08198.4325
#Mann= 3 , 0 , 0
9575.953    0.12       09575.953    0.12       010424.08    0.12       0
#XS Ineff= 2 , 0
       0                               0
Bank Sta=9575.953,10424.08
Exp/Cntr=0.3,0.1

Type RM Length L Ch R = 1 ,5990.712,96.486300,96.486300,96.486300
XS GIS Cut Line= 6
1201685.13502155617668.1491922791201695.53965585617806.912058277
1201722.47510738617935.325194296 1201828.6104331 618133.49905232
1201865.67058526618240.8837735071201887.70620449618477.231123138
#Sta/Elev= 30
 9575.93270.99379587.635 266.5319600.771258.79569623.758247.73049656.687234.0273
9673.168228.55819689.649220.45819755.933 198.2859775.887190.32799802.886182.0823
9864.368166.37979893.945161.09999947.146155.11199993.611151.571710041.47152.8486
 10056.4157.904610066.75159.427510089.09166.953410117.44167.843410151.94182.2289
10199.45194.734610229.52201.106510259.45 208.86910269.37210.0052 10292.5209.9928
10299.11 212.778 10325.4218.283210377.97 222.29610410.77226.172810424.04 226.062
#Mann= 3 , 0 , 0
 9575.93    0.12       0 9575.93    0.12       010424.04    0.12       0
#XS Ineff= 2 , 0
       0                               0
Bank Sta=9575.93,10424.04
Exp/Cntr=0.3,0.1

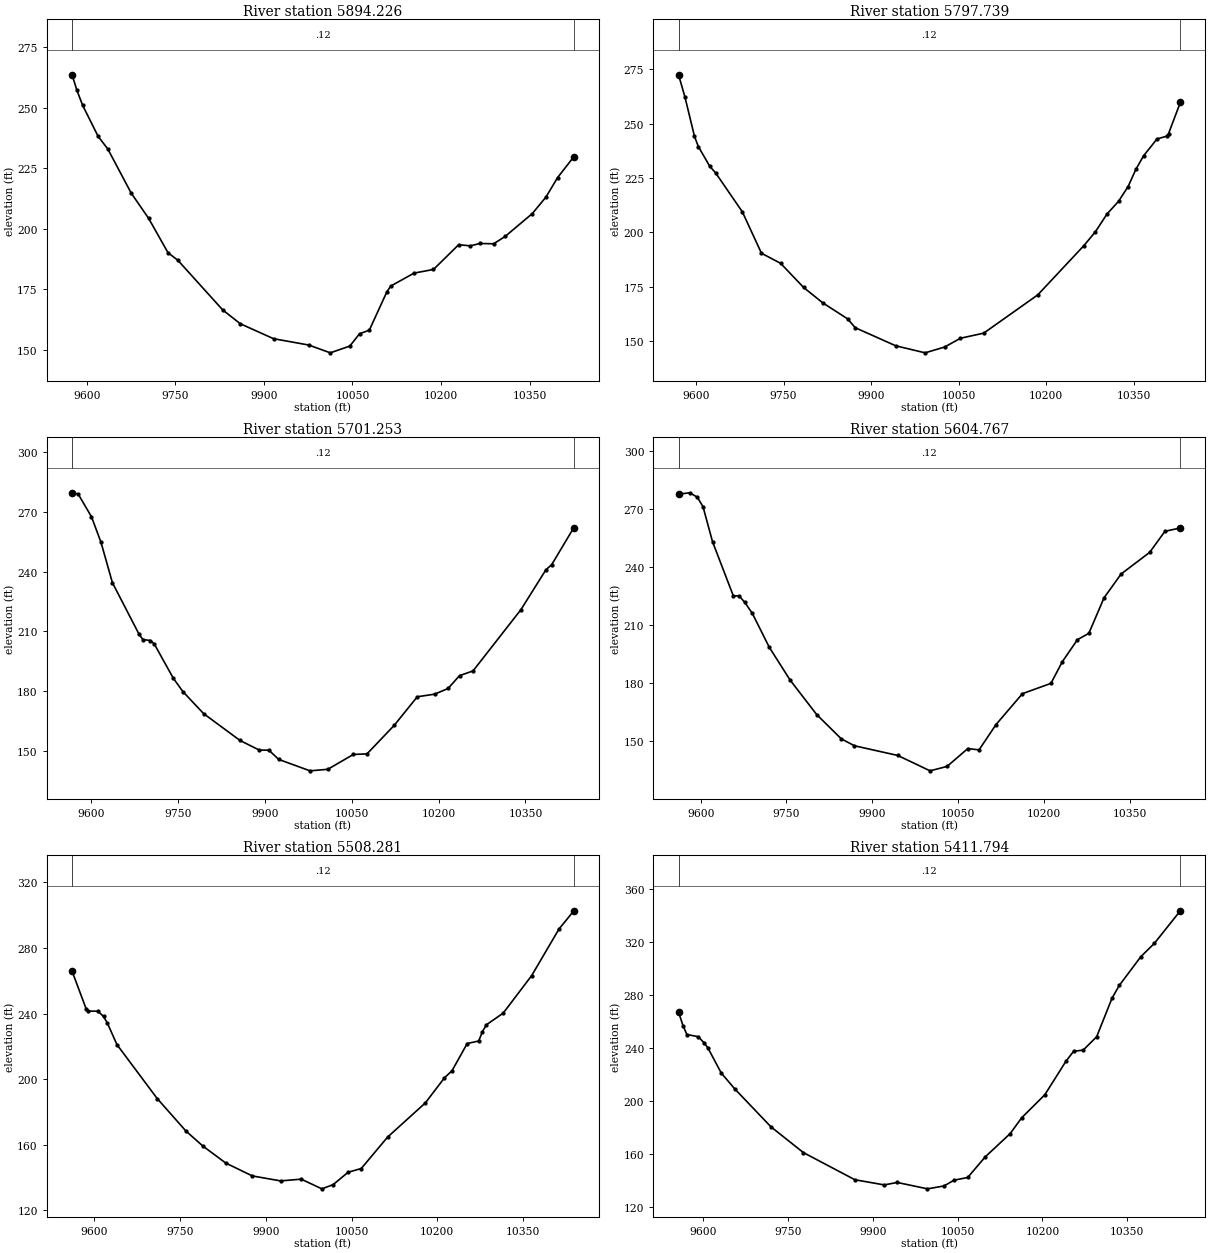
Type RM Length L Ch R = 1 ,5894.226,96.486200,96.486200,96.486200
XS GIS Cut Line= 6
1201655.29419295617675.1074730731201665.52476554617854.533187817
1201703.83795472618134.3733191261201715.82523971618257.379936076
1201721.14119395618380.6992040231201717.85913246618521.030813958
#Sta/Elev= 30
9575.168263.51579583.188257.23749593.035250.92289619.292238.10249635.703232.8896
9675.148214.73849704.767204.27529737.677190.06579754.132187.01299830.155166.4945
9859.985160.78169916.331154.60559975.991  151.9910012.43148.771110045.51151.5697
10061.99156.655710078.47158.116910108.14173.905410114.73176.321910154.29181.6769
10187.15183.184210229.84193.399610249.55192.920310265.96193.902610288.95193.7676
10308.63196.823310354.57206.267610377.56213.044510397.25221.075910424.82229.7264
#Mann= 3 , 0 , 0
9575.168    0.12       09575.168    0.12       010424.82    0.12       0
#XS Ineff= 2 , 0
       0                               0
Bank Sta=9575.168,10424.82
Exp/Cntr=0.3,0.1

Type RM Length L Ch R = 1 ,5797.739,96.486300,96.486300,96.486300
XS GIS Cut Line= 6
 1201622.3864609617662.335556345 1201624.9093146617922.132920352
1201622.20997531617986.2333851771201615.35283601618036.925877629
1201580.46403583 618212.21941205 1201549.3161607618516.867235125
#Sta/Elev= 30
9569.926272.39579580.873262.23239597.277244.10689603.839239.46889623.525230.3434
9633.368227.40489679.305 209.4899712.118190.45779744.931185.83869784.306174.7788
9817.119167.70759859.799160.33699872.934156.27929942.286147.97969992.641144.7511
10026.24147.436710053.13151.445310093.04153.789910185.63 171.33410264.78193.9684
10284.57200.353410304.36208.468510324.15214.298110340.64221.106110353.83228.9562
10367.02235.168210390.11242.9366 10406.6244.196710409.89245.365610430.09259.6894
#Mann= 3 , 0 , 0
9569.926    0.12       09569.926    0.12       010430.09    0.12       0
#XS Ineff= 2 , 0
       0                               0
Bank Sta=9569.926,10430.09
Exp/Cntr=0.3,0.1

Type RM Length L Ch R = 1 ,5701.253,96.486300,96.486300,96.486300
XS GIS Cut Line= 6
 1201564.4041074617633.2326704541201549.95175121617860.520012759
1201541.15173849617937.6536166691201529.06072079617998.363320536
1201483.64430463618174.3496641061201436.42753856618488.845610539
#Sta/Elev= 30
9566.454 279.6719576.997279.03419600.009267.60169616.446254.73439636.171234.4218
9682.196208.5031 9688.77205.8393 9701.92205.33529708.495 203.603 9741.37186.3845
9757.807179.68839793.969168.50929856.708155.04939889.963150.2128 9906.69150.1585
9923.416 145.5299977.685139.770610008.31140.544810052.55148.018110076.12148.3003
 10123.1 162.64810163.02177.044210192.96178.338510216.18181.203910236.07  187.69
10259.27190.022410342.14220.886510385.23240.918710395.17243.471210433.57262.1575
#Mann= 3 , 0 , 0
9566.454    0.12       09566.454    0.12       010433.57    0.12       0
#XS Ineff= 2 , 0
       0                               0
Bank Sta=9566.454,10433.57
Exp/Cntr=0.3,0.1

Type RM Length L Ch R = 1 ,5604.767,96.486300,96.486300,96.486300
XS GIS Cut Line= 6
1201474.30442609 617601.308275211201435.85265689617883.857790458
1201422.25098082618016.9824041521201416.46628238618050.098348628
1201401.87418039618204.5421560761201359.61309038618470.833908539
#Sta/Elev= 30
9561.303277.91659580.962278.62019594.207276.3041 9604.14271.39679620.695253.3526
9657.117225.2883 9667.05225.29089676.984222.00959690.228 216.2879720.028198.6716
9756.449181.71269802.804163.91249845.848151.33819868.936147.74689944.788142.7244
10001.08134.779610030.83137.067310067.02146.286810086.76 145.62810116.46158.7335
10162.69174.715210212.42180.019210232.32191.213810258.85202.640510278.75205.9049
10305.29224.280410335.24236.617410385.15247.808710411.77258.6924 10438.7260.4207
#Mann= 3 , 0 , 0
9561.303    0.12       09561.303    0.12       0 10438.7    0.12       0
#XS Ineff= 2 , 0
       0                               0
Bank Sta=9561.303,10438.7
Exp/Cntr=0.3,0.1

Type RM Length L Ch R = 1 ,5508.281,96.486300,96.486300,96.486300
XS GIS Cut Line= 6
1201387.19780338617616.0712808981201330.01557989 617908.72447255
1201322.82095065617982.9889177631201325.06245016618098.958721003
1201319.84424396618174.3084931281201263.48989294618482.938309895
#Sta/Elev= 30
9560.917265.87829585.844242.63039589.196241.52849605.953241.45589616.007238.2682
 9622.71234.20869639.467221.09319709.847188.24199760.059168.44469790.022159.2016
9829.972 148.8759876.408141.03849925.851138.0155 9961.98139.07179998.074133.1704
10017.77135.733810044.02143.274510067.03145.561410113.07164.699910179.22185.5633
10212.51200.797410225.82205.152810252.46221.761610272.49223.280710279.18229.0405
10285.88233.140610315.47240.290810365.35263.212210413.05 291.545 10439.1 302.678
#Mann= 3 , 0 , 0
9560.917    0.12       09560.917    0.12       0 10439.1    0.12       0
#XS Ineff= 2 , 0
       0                               0
Bank Sta=9560.917,10439.1
Exp/Cntr=0.3,0.1

Type RM Length L Ch R = 1 ,5411.794,96.486300,96.486300,96.486300
XS GIS Cut Line= 6
1201349.17462787617603.1979984021201261.41304543617956.690461231
1201247.92481144 617996.58308734 1201217.8711144618058.993013854
1201201.88411697 618103.142801221201105.13154175 618455.88755068
#Sta/Elev= 30
9555.837266.9687 9563.82256.66329570.581 250.0059590.864248.36319601.005243.7033
9607.766239.92999631.429220.94169655.092 209.038 9719.32180.30349776.787160.8004
9868.059140.25559920.061136.36289942.977138.21399996.548133.389710025.74135.5626
10043.43139.909610067.85141.988510098.73157.526310142.96 175.12810163.37187.1201
 10204.2204.451210241.62229.768210255.23 237.32110272.24238.244210296.05248.3143
10323.27277.475710336.22287.1618 10374.3308.851910398.24318.884810444.17 343.509
#Mann= 3 , 0 , 0
9555.837    0.12       09555.837    0.12       010444.17    0.12       0
#XS Ineff= 2 , 0
       0                               0
Bank Sta=9555.837,10444.17
Exp/Cntr=0.3,0.1

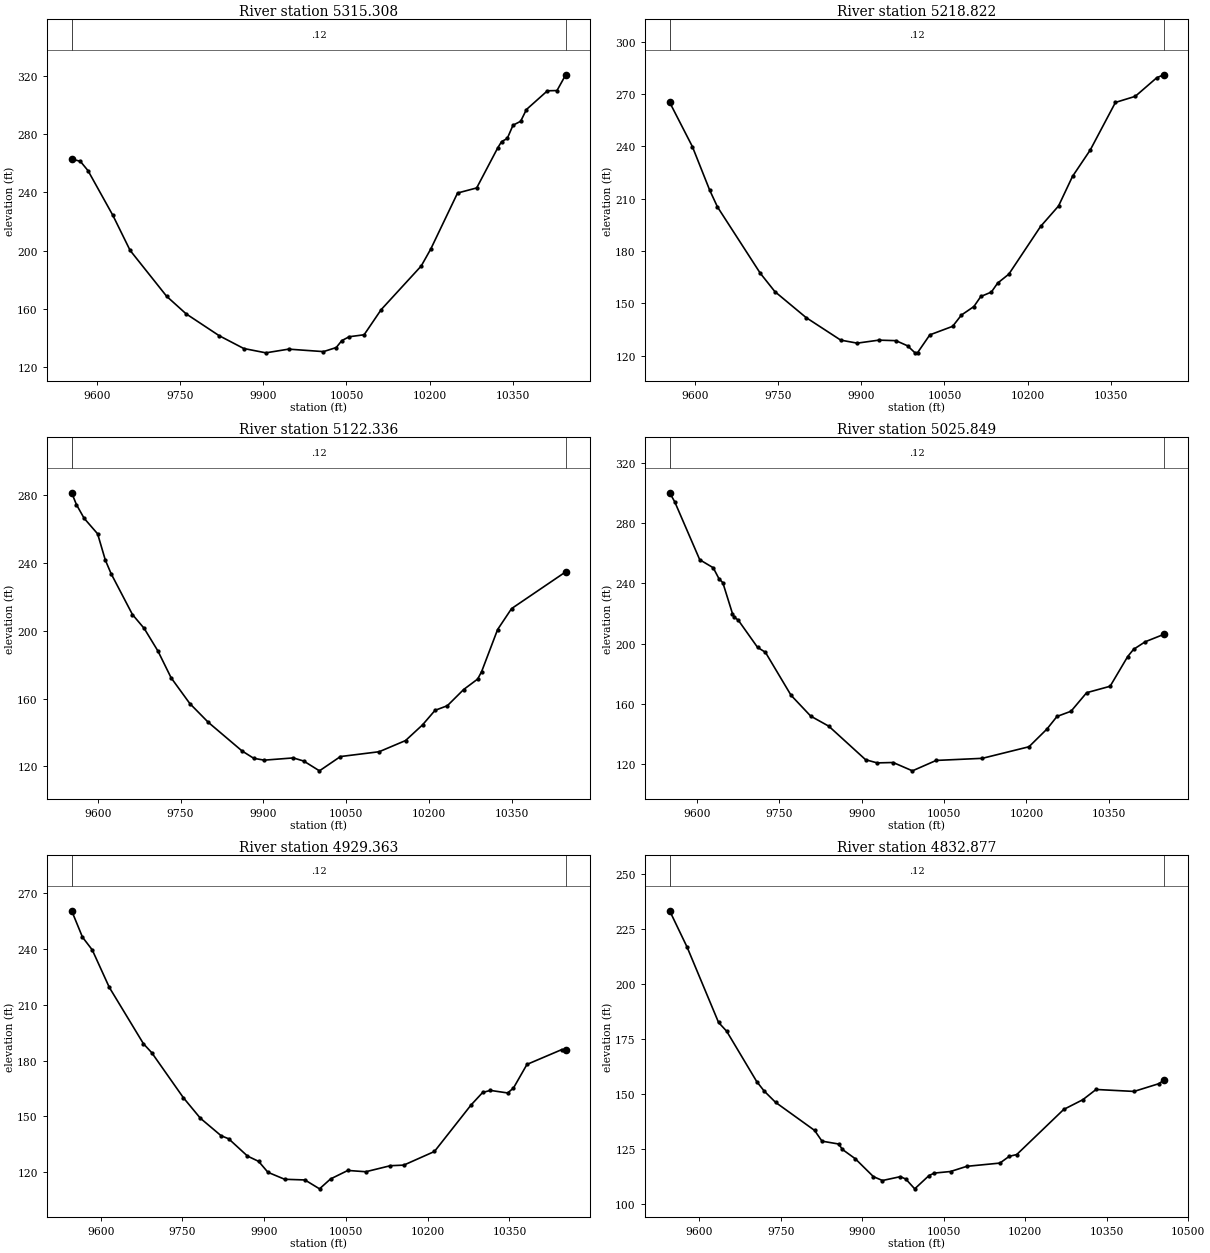
Type RM Length L Ch R = 1 ,5315.308,96.486200,96.486200,96.486200
XS GIS Cut Line= 6
1201276.46123873617579.6960498471201231.42078844 617717.91999385
1201153.49846739 617923.94628235  1201143.718036617964.887022342
1201128.53691086618086.1934945371201018.40147443618429.775017874
#Sta/Elev= 30
9554.457262.97559570.071 261.4079583.874 255.0069628.732224.22639659.787200.1443
9725.705168.53839760.847 156.4559820.477141.41019864.819132.59599904.661129.6106
9945.731132.155610008.61130.454710031.62133.257610041.68 138.03410055.09140.6964
10081.91142.045910112.69 159.35210184.92189.378410202.17201.089310250.45239.5874
10284.94243.090510322.88270.628910329.78274.928810340.13277.160410350.47286.2615
10364.27 288.96210374.62297.028310412.55309.9476 10429.8310.100310445.59320.9628
#Mann= 3 , 0 , 0
9554.457    0.12       09554.457    0.12       010445.59    0.12       0
#XS Ineff= 2 , 0
       0                               0
Bank Sta=9554.457,10445.59
Exp/Cntr=0.3,0.1

Type RM Length L Ch R = 1 ,5218.822,96.486300,96.486300,96.486300
XS GIS Cut Line= 6
1201245.80752745617575.4116090231201143.43212089617831.824163563
1201087.39944851617931.4466061061201018.11849855618015.231218289
1200966.91779387618097.183906069 1200848.8930544618367.290771173
#Sta/Elev= 30
9554.388265.31439595.338 239.932 9626.59214.9232 9640.61205.28419717.896167.2088
9744.193156.67969800.454141.79969862.984 128.836 9892.71127.10659931.666128.8303
9962.609128.5337 9983.59125.57029996.995121.542510001.74 121.71810023.72131.8574
10064.89136.761610080.67143.217410103.23148.120710115.69153.888310134.66156.4019
10146.05161.567810166.26166.708810223.47194.052710255.89205.820210281.09222.7968
10313.09237.941510358.52265.2409 10394.3268.742610433.13 279.43610445.61281.1128
#Mann= 3 , 0 , 0
9554.388    0.12       09554.388    0.12       010445.61    0.12       0
#XS Ineff= 2 , 0
       0                               0
Bank Sta=9554.388,10445.61
Exp/Cntr=0.3,0.1

Type RM Length L Ch R = 1 ,5122.336,96.486300,96.486300,96.486300
XS GIS Cut Line= 6
1201205.59829186617520.8067391281201096.67672174617774.815390851
1201040.35953135617854.2212189031200945.94734404617939.911679733
1200892.72935419618006.8255754311200759.16790962618282.204392628
#Sta/Elev= 30
9552.975281.31899561.595274.32929575.528266.26799599.912257.12419613.845241.6641
9624.296233.65769662.983209.53189684.177201.3742 9709.11188.02039732.959172.2394
9766.832157.06169800.207146.0206 9861.24129.15859882.473124.80469901.506123.7248
9954.069 125.0459972.915123.193110001.34117.428110039.33125.849210109.42128.6925
10157.14135.271910187.84144.504910210.56153.097310232.74155.795810262.31165.3653
10287.66171.525510294.88175.971710323.77 200.73310348.99 213.04510447.05234.7278
#Mann= 3 , 0 , 0
9552.975    0.12       09552.975    0.12       010447.05    0.12       0
#XS Ineff= 2 , 0
       0                               0
Bank Sta=9552.975,10447.05
Exp/Cntr=0.3,0.1

Type RM Length L Ch R = 1 ,5025.849,96.486300,96.486300,96.486300
XS GIS Cut Line= 6
1201109.65722749617431.6761432331201009.72853849617678.439154935
1200960.07239222617771.2657393571200838.24263466617968.236745992
1200782.32034487618083.1042905741200716.42162333618238.962628619
#Sta/Elev= 30
 9549.84300.14439559.103294.13929604.688255.68749629.234250.37369639.753243.0754
9646.766240.43689664.299 219.9469667.658217.54049674.819215.61359710.011197.5394
9724.371194.24469771.041165.71879806.942 151.8729839.857145.19239906.904122.9379
9928.023120.82439957.135 121.0869992.273115.552210035.48122.463610119.58 123.858
10204.63131.538210237.47143.335410255.71151.663610281.25155.112710309.74167.4246
10352.49171.701110384.55191.434310395.23 196.217 10416.6201.265910450.16206.1237
#Mann= 3 , 0 , 0
 9549.84    0.12       0 9549.84    0.12       010450.16    0.12       0
#XS Ineff= 2 , 0
       0                10212.01       0
Bank Sta=9549.84,10450.16
Exp/Cntr=0.3,0.1

Type RM Length L Ch R = 1 ,4929.363,96.486300,96.486300,96.486300
XS GIS Cut Line= 6
1200966.44942811617375.3202685621200861.45513268617675.263803439
1200837.86029518617758.0455756791200817.76381945617850.828735335
 1200800.0377853617908.6938681721200672.07986147618231.401933016
#Sta/Elev= 30
9546.742260.43719566.538246.27769584.425239.45779615.772219.30319678.467 189.012
9693.554184.25049751.612160.06949782.826149.02849820.907139.62629834.755137.9862
9869.304128.70369889.773125.8458 9906.83119.98149937.534116.23339974.672115.8738
 10001.5111.098610021.66116.404410053.48120.976710086.34120.279810131.48123.5252
10156.01123.828610212.33131.158610279.53156.142810300.75162.8489 10314.9 163.969
10346.73162.591310357.34 165.257 10382.1177.927310445.77185.856510453.25185.6023
#Mann= 3 , 0 , 0
9546.742    0.12       09546.742    0.12       010453.25    0.12       0
#XS Ineff= 2 , 0
       0                10197.89       0
Bank Sta=9546.742,10453.25
Exp/Cntr=0.3,0.1

Type RM Length L Ch R = 1 ,4832.877,96.486300,96.486300,96.486300
XS GIS Cut Line= 6
1200850.93072622617350.7893405441200751.47866477617661.889314017
 1200736.5803831617738.5682224931200727.11432844 617854.39447267
 1200711.1656251617927.1660847361200606.04985853618223.056543115
#Sta/Elev= 30
9545.132233.47559577.337216.89199635.172182.64079650.091178.64749705.522155.6895
 9719.38151.35629740.166146.26249812.006 133.4889825.659128.59439856.376127.2898
9863.202124.8256 9886.86120.6054 9920.38112.42989937.005 110.6789970.081112.4356
9979.969  111.339996.386106.885110022.66 112.93210032.54114.061210062.28114.7737
 10092.3117.136610153.24118.610110170.46121.685110184.24122.494510270.77143.0407
10305.79147.4437 10330.3152.1226 10400.2 151.23310445.86154.755210454.86156.3443
#Mann= 3 , 0 , 0
9545.132    0.12       09545.132    0.12       010454.86    0.12       0
#XS Ineff= 2 , 0
       09882.907        10170.88       0
Bank Sta=9545.132,10454.86
Exp/Cntr=0.3,0.1