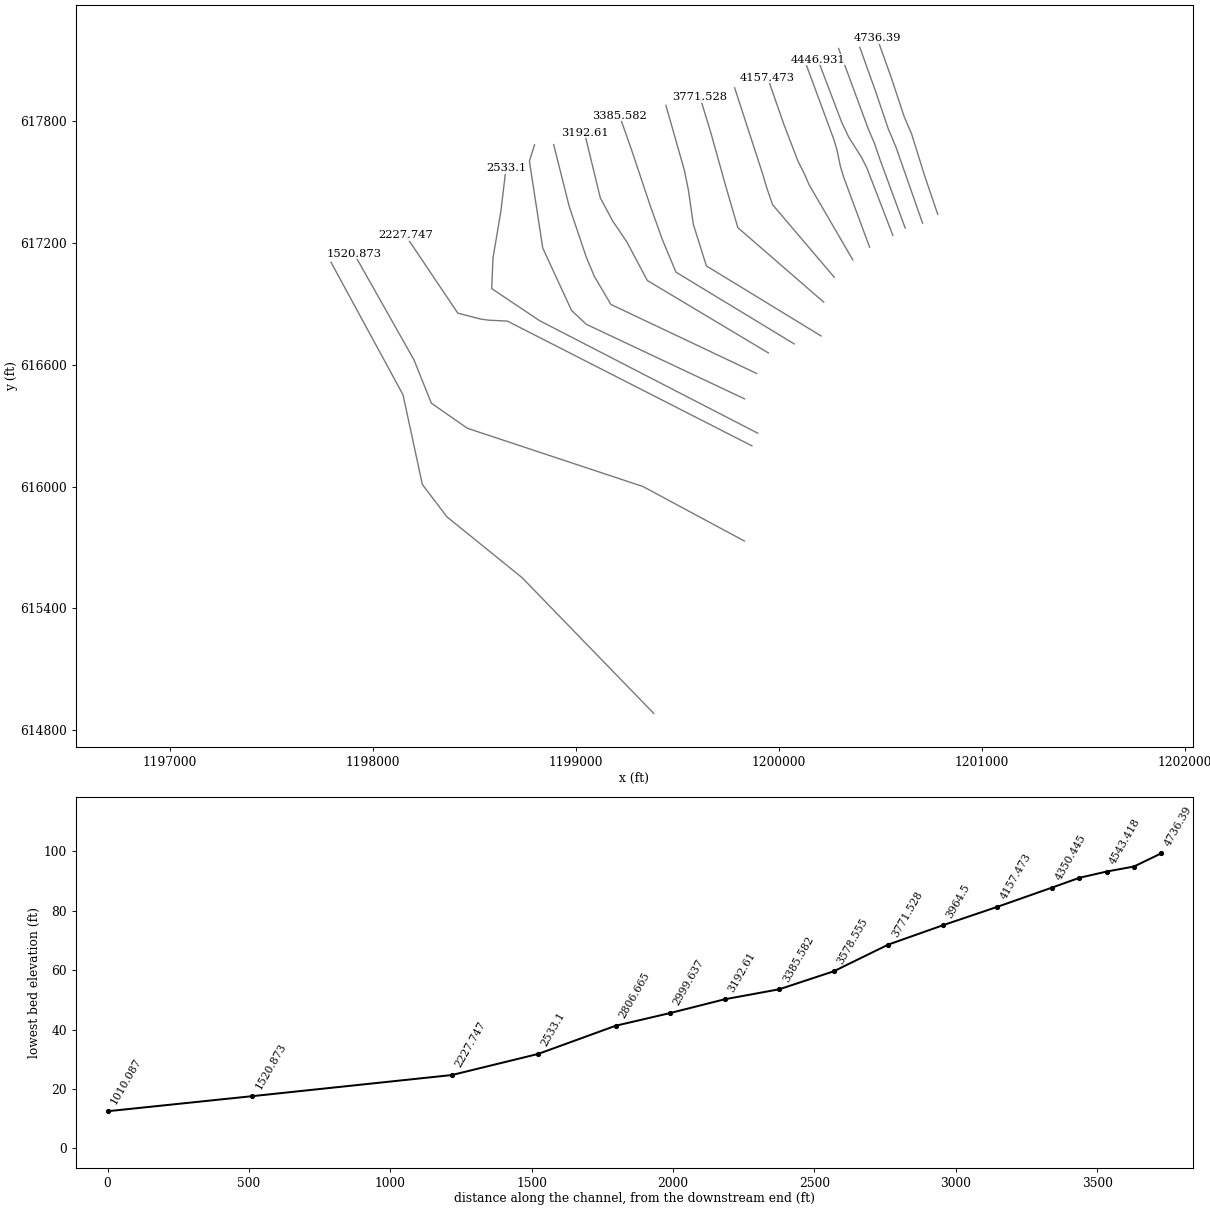
HEC-RAS study 148_ras.prj: 148

--- 148_ras.g01 (geometry) --- (continued)

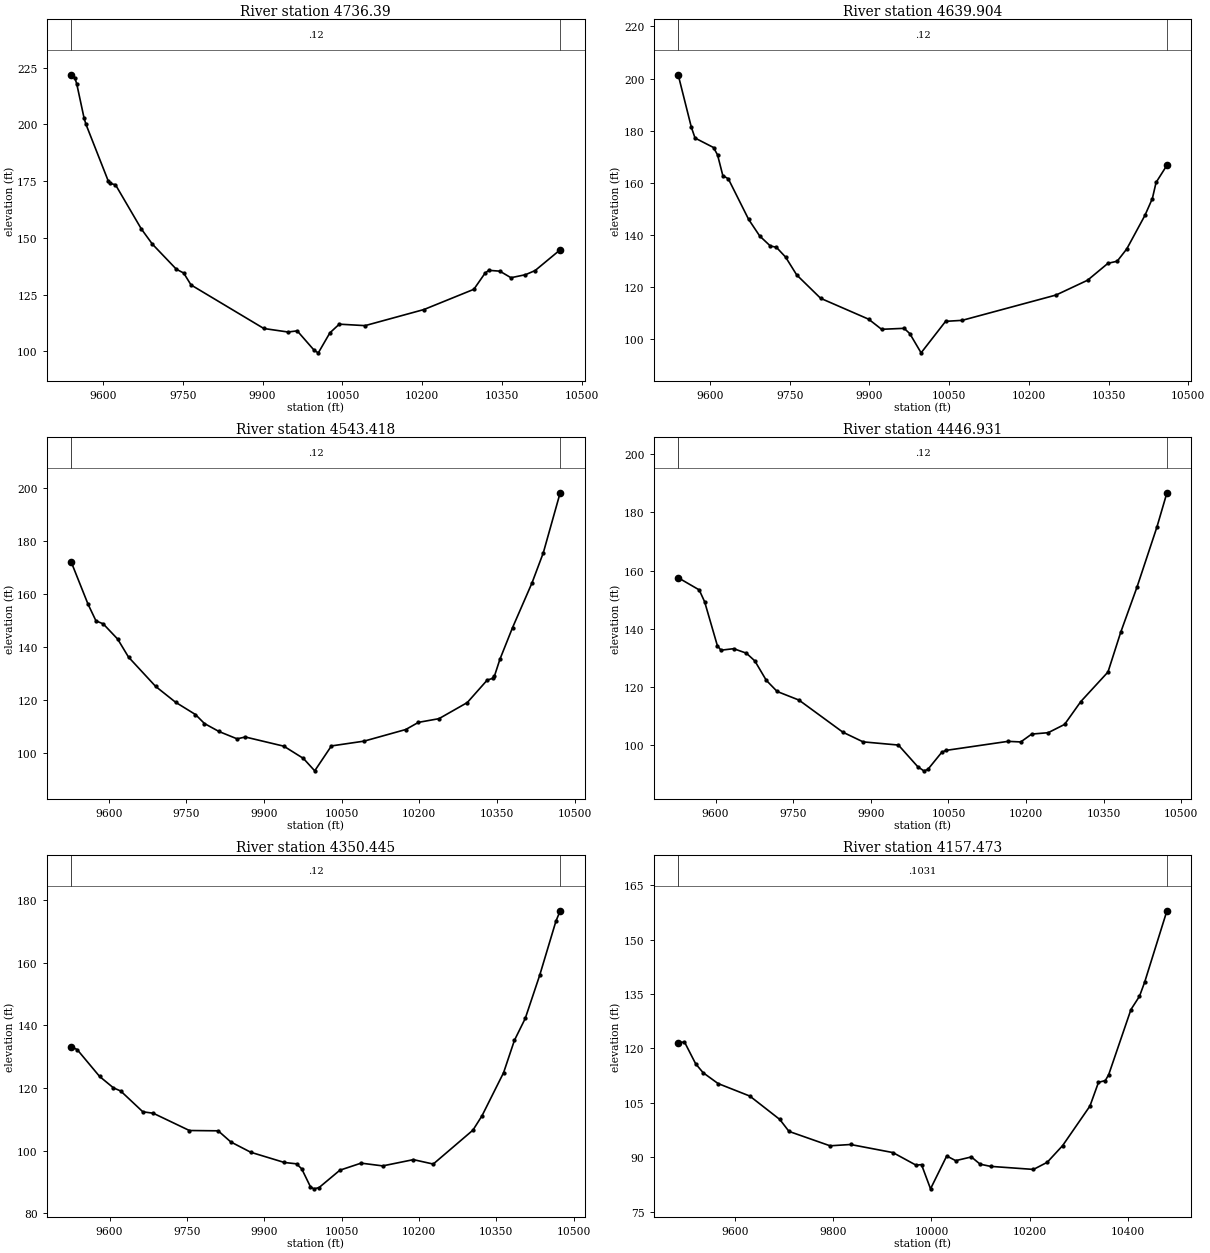
Type RM Length L Ch R = 1 , 4736.39,96.486200,96.486200,96.486200
XS GIS Cut Line= 6
1200783.49961627617342.3695203421200719.18010155617531.233228338
1200654.41294719617739.2783659551200618.18039937617823.048864492
1200556.01001051618011.3882082411200485.07458535618209.773452199
#Sta/Elev= 30
9541.082221.83029547.537220.39819551.003217.91139564.866202.72139568.332200.0498
9609.922175.22339613.388173.94669623.786173.39549672.308153.92199693.103147.2129
 9738.16136.14499751.925 134.473 9765.67129.2293 9902.39110.03099947.785108.4796
9965.118108.98699997.298100.339410004.7599.3037210026.51108.1284 10044.1111.9378
10092.57111.292410203.13118.387110296.82127.303310317.73134.374910324.69135.6612
 10345.6135.295910366.51132.406310393.66133.7289 10411.8135.550410458.92144.7069
#Mann= 3 , 0 , 0
9541.082    0.12       09541.082    0.12       010458.92    0.12       0
#XS Ineff= 2 , 0
       09912.676        10123.27       0
Bank Sta=9541.082,10458.92
Exp/Cntr=0.3,0.1

Type RM Length L Ch R = 1 ,4639.904,96.486300,96.486300,96.486300
XS GIS Cut Line= 6
1200708.69353584617298.8088423931200578.60858353617670.552150129
1200553.64833372 617730.64185524 1200538.6665554617766.455393871
1200478.68610968617943.6687160131200399.56911931618164.966148621
#Sta/Elev= 30
9540.086201.47219564.902181.34319571.854177.21889606.613173.58749614.207170.7554
 9624.14162.80829634.421161.60529672.656146.05129693.511 139.6769713.537135.8396
9724.794135.36919742.174131.60599763.203124.73749808.216115.7837 9898.59107.7766
9922.921103.90619965.309104.27729975.967102.26199997.28394.8837710043.37106.9592
10074.54107.338210251.34 117.05310310.57122.7165 10348.9129.195110366.32130.0105
10384.31134.708910418.58147.595710432.52154.043910439.49160.199510459.93166.7932
#Mann= 3 , 0 , 0
9540.086    0.12       09540.086    0.12       010459.93    0.12       0
#XS Ineff= 2 , 0
       09944.817        10119.53       0
Bank Sta=9540.086,10459.93
Exp/Cntr=0.3,0.1

Type RM Length L Ch R = 1 ,4543.418,96.486300,96.486300,96.486300
XS GIS Cut Line= 6
1200623.11162871617274.4298009641200499.58592432617610.152480541
1200470.40077131 617696.058602981200460.11359945617718.677173914
 1200442.5580552617759.5150633341200294.63689558618159.913131525
#Sta/Elev= 30
 9527.69171.86679559.772156.14089575.131149.82539589.114148.69949617.081142.9449
9638.056136.14369690.494125.06869728.949119.10529767.403114.46089784.883111.0504
 9812.85108.05039847.808105.2829 9863.81105.9728 9938.23102.50319976.14597.86525
9997.91293.1951810030.15102.599610093.42104.413910173.87108.800410198.35111.4982
10238.05112.893610292.79118.977610331.26127.462910342.19128.143710345.25128.9661
10355.74135.275510380.22147.266210417.93164.196510439.68 175.518 10472.3198.1912
#Mann= 3 , 0 , 0
 9527.69    0.12       0 9527.69    0.12       0 10472.3    0.12       0
#XS Ineff= 2 , 0
       09918.746        10083.09       0
Bank Sta=9527.69,10472.3
Exp/Cntr=0.3,0.1

Type RM Length L Ch R = 1 ,4446.931,96.486300,96.486300,96.486300
XS GIS Cut Line= 6
 1200562.3774804617238.2514633651200434.36730092617570.242837334
1200406.57260376617625.115849143 1200344.8363222617722.420163017
1200310.36605137617794.8592385751200192.58569185618104.959212337
#Sta/Elev= 30
9527.717 157.5179568.357153.3259 9578.87 149.232  9603.4134.17739610.409132.5834
9634.939 133.1079659.468131.56639675.853128.90369698.015122.22379719.041118.3841
9761.092115.43579846.011104.3834 9885.06101.0561 9953.3799.95742 9990.7592.51179
10002.4391.0889310010.1691.5553510037.2297.4876210045.1698.1175510165.08101.2294
10189.79101.028710210.97103.733910242.74104.206810274.45 107.05110305.93114.9354
10358.38125.084910382.86138.694810414.34154.233610452.81174.8739 10472.3186.7366
#Mann= 3 , 0 , 0
9527.717    0.12       09527.717    0.12       0 10472.3    0.12       0
#XS Ineff= 2 , 0
       09926.113        10085.29       0
Bank Sta=9527.717,10472.3
Exp/Cntr=0.3,0.1

Type RM Length L Ch R = 1 ,4350.445,192.972600,192.972600,192.972600
XS GIS Cut Line= 6
1200447.58996595  617180.36810671200319.61628628617525.905555141
1200303.53452714617579.2138555291200286.33951612617661.607055608
1200271.02216031617712.4222601781200137.02555982618074.725923845
#Sta/Elev= 30
9526.149133.1952 9537.51132.20819580.854123.65869607.627120.03099621.651119.0284
9664.621112.38919684.756111.92959754.873106.41569810.744106.31339835.131102.7708
9873.87599.474529938.91296.217559962.63595.777989972.69994.179089989.47188.50077
9996.18187.7969110006.2388.1878410046.6893.74384 10087.895.9998910129.7895.12009
10189.2597.1170910227.7395.7044210304.68106.530910322.17111.080810364.15124.8828
10385.14135.196710406.13142.194210434.11155.944310465.59173.214710473.85176.5483
#Mann= 3 , 0 , 0
9526.149    0.12       09526.149    0.12       010473.85    0.12       0
#XS Ineff= 2 , 0
       09931.942        10094.45       0
Bank Sta=9526.149,10473.85
Exp/Cntr=0.3,0.1

Type RM Length L Ch R = 1 ,4157.473,192.972500,192.972500,192.972500
XS GIS Cut Line= 6
1200364.89756575617117.5577638751200149.27342868617488.271027237
1200128.64707011617536.3506204631200093.30536747617607.383865386
1200024.83444947617786.4059558361199945.08078226618014.675770909
#Sta/Elev= 30
9484.993121.57919497.841121.77619520.613115.76069535.795113.31219566.159110.3325
9630.681106.88589691.669100.44159710.38697.152829793.88693.185799835.63693.54711
9921.76391.321469968.875 87.84789979.885 88.00919998.23481.3350110031.1690.38615
10049.3789.0998610081.2990.1207210099.0388.1288610120.2287.5261410207.59 86.6818
10235.54 88.645310266.8393.2338910322.43104.132310339.81110.664910353.71 111.156
10360.66112.818210405.84130.718910423.22134.381110433.64138.227710479.02157.9155
#Mann= 3 , 0 , 0
9484.993  0.1031       09484.993  0.1031       010479.02  0.1031       0
#XS Ineff= 2 , 0
       09918.611        10084.39       0
Bank Sta=9484.993,10479.02
Exp/Cntr=0.3,0.1

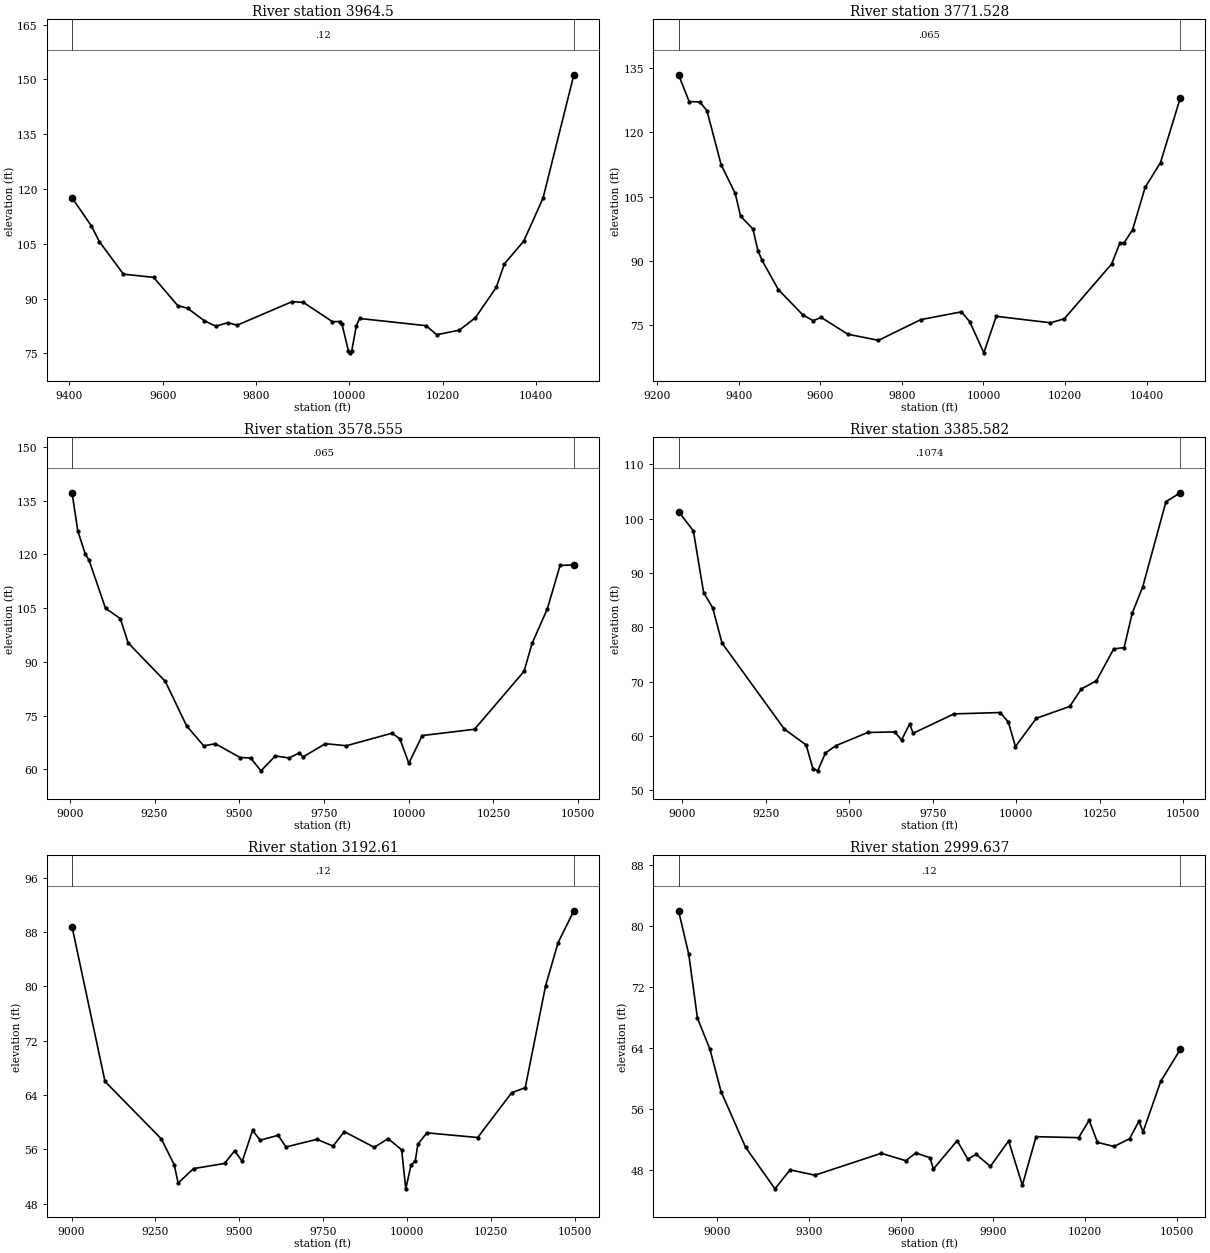
Type RM Length L Ch R = 1 ,  3964.5,192.972600,192.972600,192.972600
XS GIS Cut Line= 6
1200273.75173244617031.6202638751199969.53373423617389.457327887
1199942.24652091617468.1193353981199930.49012262617506.886998475
1199922.40531579 617535.434424461199782.32028881617965.844168827
#Sta/Elev= 30
9405.552117.56689446.801109.91169464.026   105.69515.70196.668529580.29495.80016
9631.96988.083219653.19887.332729688.65583.948389713.78782.418089739.30783.38583
9759.56882.696149876.99989.133119901.308   88.959963.74783.654519980.88983.70043
9984.31782.928249998.03175.6241910001.4275.1208710004.84 75.500710015.0782.57783
 10021.984.5357710164.3782.5592710187.4480.0875510235.7481.3230210270.2484.73574
 10315.193.0900710332.3599.4885110373.75105.695110415.15117.461510481.31151.2807
#Mann= 3 , 0 , 0
9405.552    0.12       09405.552    0.12       010481.31    0.12       0
#XS Ineff= 2 , 0
       09918.204        10074.08       0
Bank Sta=9405.552,10481.31
Exp/Cntr=0.3,0.1

Type RM Length L Ch R = 1 ,3771.528,192.972600,192.972600,192.972600
XS GIS Cut Line= 6
1200221.66839907616909.2244305461199798.01655397617276.505215928
1199746.01185432617455.1848806291199740.12173295617475.243655905
1199665.23836359617743.5726940331199611.50032425617919.893678948
#Sta/Elev= 30
9252.214133.43589278.338127.1875 9304.39127.10299321.759125.08859356.818112.4376
9391.232 105.7769404.259100.47859434.653 97.50059446.97292.420099456.98990.17306
9497.05783.350819557.15977.447559582.28576.113869602.23676.867689667.34772.95483
9742.47571.526759846.863 76.37279945.95578.173899966.45775.86406   1000168.61409
10031.3677.13102 10164.275.6198310198.2676.5520910314.18 89.305310334.76 94.2368
10345.0594.2943510365.6397.27439 10396.5 107.18210434.22112.979110482.82128.0566
#Mann= 3 , 0 , 0
9252.214   0.065       09252.214   0.065       010482.82   0.065       0
#XS Ineff= 2 , 0
       09931.861        10063.28       0
Bank Sta=9252.214,10482.82
Exp/Cntr=0.3,0.1

Type RM Length L Ch R = 1 ,3578.555,192.972600,192.972600,192.972600
XS GIS Cut Line= 6
1200208.64756575 616742.557763861199643.17892438617087.773934409
1199578.93842354617292.0177895721199554.37004066617461.626977175
1199534.82662642617558.3932714311199443.41740885617879.548671558
#Sta/Elev= 30
9006.616137.19539023.524126.54989045.238120.1816 9056.77118.36729105.376 104.972
9149.024102.09289172.08795.323279281.67584.586179344.63872.193329395.03466.60132
9429.62967.173819502.663 63.33089533.41463.208819564.16659.622839606.44963.77484
9646.86463.221829677.72264.631759688.18263.488229754.38167.200939816.16266.62597
9950.93870.126139974.12768.5523110000.4961.7344910040.1169.4675310194.4271.21711
10340.5587.3775710364.5795.2375110409.16104.7697 10446.9116.923610487.62117.0727
#Mann= 3 , 0 , 0
9006.616   0.065       09006.616   0.065       010487.62   0.065       0
#XS Ineff= 2 , 0
       09936.929        10050.84       0
Bank Sta=9006.616,10487.62
Exp/Cntr=0.3,0.1

Type RM Length L Ch R = 1 ,3385.582,192.972500,192.972500,192.972500
XS GIS Cut Line= 6
1200075.83506572 616703.49526386 1199493.1621643617057.066702619
1199425.55334866617218.7002425491199364.01736137617390.930463672
1199277.97333416617648.6894815561199214.84316376617828.715459079
#Sta/Elev= 30
8988.993101.3235 9033.3897.761649064.08186.393759090.94583.62948 9119.2277.09273
9305.851 61.24879371.09158.319919391.16353.981839405.62953.561939428.65556.83282
9459.35658.180979555.297 60.62499635.88760.731539656.78159.247839680.663 62.1804
 9691.4160.485189813.685 64.0538 9952.2664.300779976.65362.506439997.56258.02703
10060.0163.2401210160.3265.42929 10194.968.6490310239.8770.1341610291.7576.01636
   1032376.2642510347.3382.6370710378.6287.4509410448.16103.131810491.19104.7771
#Mann= 3 , 0 , 0
8988.993  0.1074       08988.993  0.1074       010491.19  0.1074       0
#XS Ineff= 2 , 0
       09879.226        10060.72       0
Bank Sta=8988.993,10491.19
Exp/Cntr=0.3,0.1

Type RM Length L Ch R = 1 , 3192.61,192.972600,192.972600,192.972600
XS GIS Cut Line= 6
 1199948.2308991616659.2244305311199351.87673241617015.995263875
1199250.73309183617206.5927929881199180.29674584617310.625075817
1199119.97820431617423.8340493291199041.98089907617745.161930531
#Sta/Elev= 30
9001.44388.777169099.59266.00903 9267.8157.532049306.04153.717659317.51151.04001
9363.38853.174379455.71353.934269485.72855.785799508.66754.261269539.25258.78828
9562.19157.364619615.71558.081219638.65456.360449731.06557.488189779.34956.49157
9812.77758.621059901.91756.309959943.27357.58515 9983.6255.948759995.82950.19628
10011.9253.7570710023.9554.2263110031.9756.7573610058.7858.4434610210.1757.75264
10311.4564.3450410351.9765.0953910412.7480.1325910449.8786.4515110496.8391.14187
#Mann= 3 , 0 , 0
9001.443    0.12       09001.443    0.12       010496.83    0.12       0
#XS Ineff= 2 , 0
       09862.637        10076.94       0
Bank Sta=9001.443,10496.83
Exp/Cntr=0.3,0.1

Type RM Length L Ch R = 1 ,2999.637,192.972600,192.972600,192.972600
XS GIS Cut Line= 6
1199890.93923244616557.6619305311199172.49126643616897.912548736
1199090.82401279617035.9768388871199050.66166806617131.879743934
1198967.08644184617380.0307272971198890.21809623617686.142547533
#Sta/Elev= 30
 8874.22  81.9718907.65376.25872 8935.8667.922328976.62663.841289012.92858.29382
9092.79251.008659188.81145.557639237.99848.044779319.11947.346689535.67250.21137
9615.53549.245219648.20750.249169694.59349.635679705.69548.147449783.22951.86517
9818.10849.434359845.01650.077439891.58948.497949951.06151.835259995.92746.02999
10040.6452.3882710179.5252.2575110213.8454.5398710240.9151.6447110295.0351.10259
10345.77 52.126910376.2154.4194510389.7453.0233610447.2559.6216210511.2563.82486
#Mann= 3 , 0 , 0
 8874.22    0.12       0 8874.22    0.12       010511.25    0.12       0
#XS Ineff= 2 , 0
       09886.698        10071.85       0
Bank Sta=8874.22,10511.25
Exp/Cntr=0.3,0.1

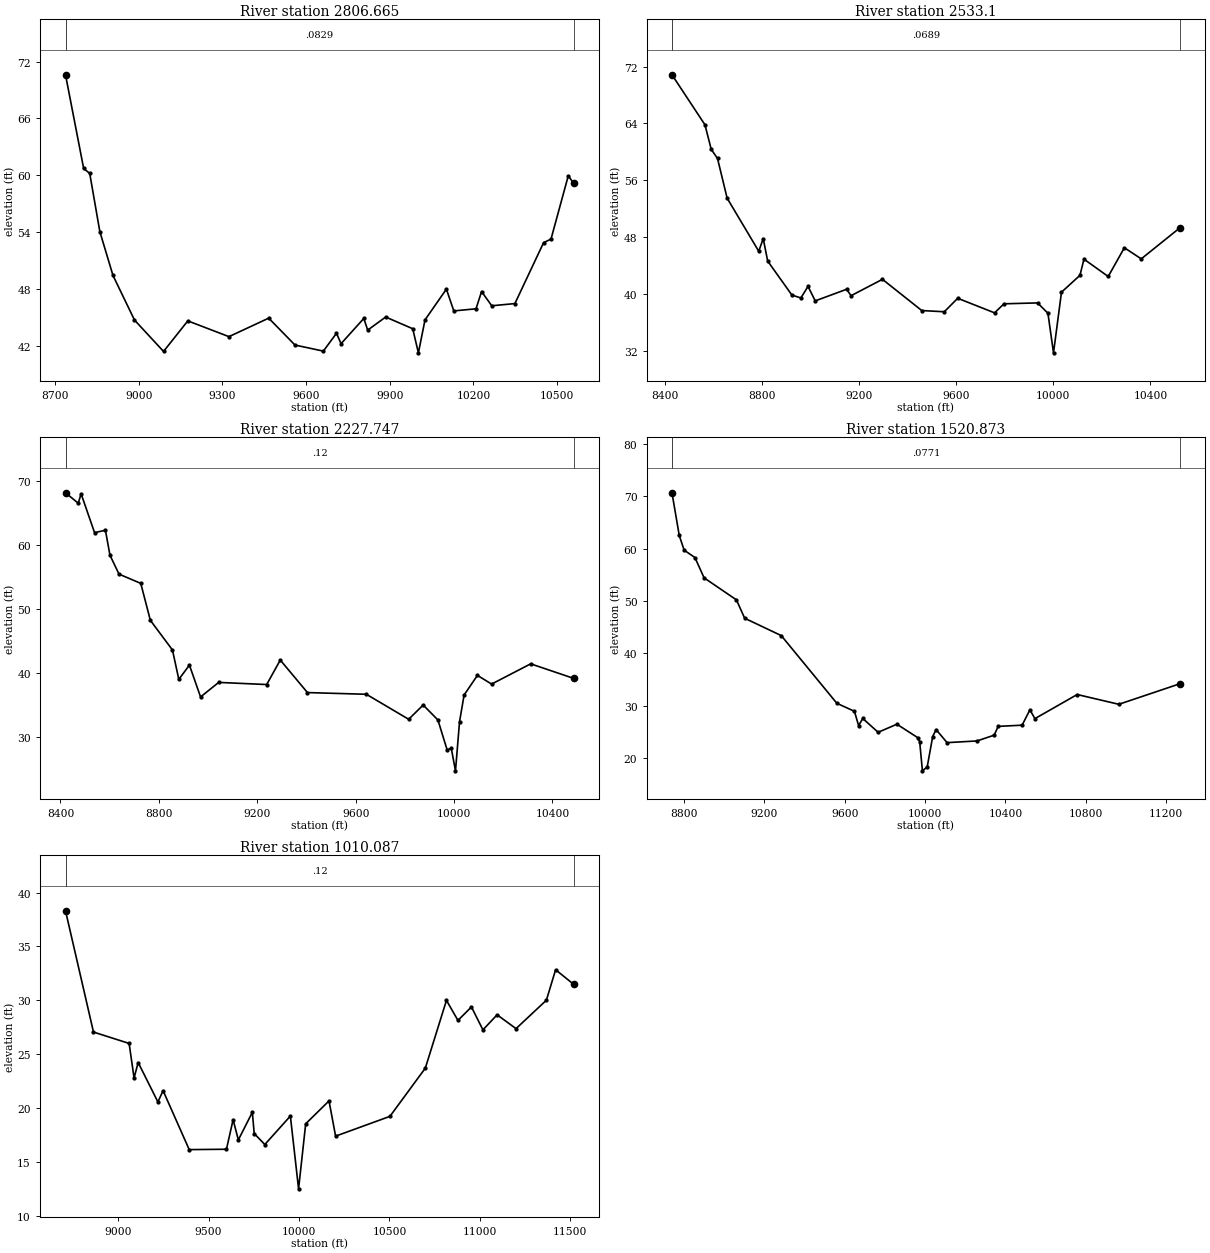
Type RM Length L Ch R = 1 ,2806.665,273.564300,273.564300,273.564300
XS GIS Cut Line= 6
1199831.04339907616432.6619305311199050.59549451616800.330283448
1198978.36726791616868.3085280511198836.48266852617175.833275467
1198770.62680894617604.5390809031198795.95202273617684.735591218
#Sta/Elev= 30
8737.22470.608388802.33660.722318824.09660.200748860.36354.059858907.50949.43561
8984.66144.731649088.84341.420899175.883 44.64419323.38742.981789466.01744.93197
 9560.3142.095219661.98941.455319709.13843.336569725.55342.241029807.16644.90334
9821.046 43.67049885.56545.051369982.53443.81693 10002.941.2729510026.6744.75409
10103.3447.9950710129.89 45.695210209.5645.9207910229.4747.7394510265.99 46.2392
10348.9746.4688510451.8752.8937210478.5453.2754110540.4759.9543110559.36 59.1692
#Mann= 3 , 0 , 0
8737.224  0.0829       08737.224  0.0829       010559.36  0.0829       0
#XS Ineff= 2 , 0
       09870.281        10068.22       0
Bank Sta=8737.224,10559.36
Exp/Cntr=0.3,0.1

Type RM Length L Ch R = 1 ,  2533.1,305.353400,305.353400,305.353400
XS GIS Cut Line= 6
1199896.14756575616263.3910972031198820.62673244616818.078597188
1198584.73001584616976.0727750661198591.04026535617126.302890033
1198629.93117681617356.914768383 1198655.2563906617569.365172878
#Sta/Elev= 30
8429.846 70.83788565.68363.815458591.52360.366218617.36359.091278656.99753.51402
 8787.1746.059238805.62847.831948824.08544.675718923.75539.907588960.66939.50248
8990.20141.124479019.73339.092169148.93440.718469167.39139.820799296.59242.11787
9458.65237.732449551.30337.564259606.67539.457269758.35437.410889797.19738.68051
9935.42338.806889978.11137.35767 10001.131.7960310033.9340.3107810109.9342.67321
10126.5644.9489410226.3842.5155810292.9246.5527510362.4144.9901710522.0849.36399
#Mann= 3 , 0 , 0
8429.846  0.0689       08429.846  0.0689       010522.08  0.0689       0
#XS Ineff= 2 , 0
       09809.849        10069.65       0
Bank Sta=8429.846,10522.08
Exp/Cntr=0.3,0.1

Type RM Length L Ch R = 1 ,2227.747,706.873800,706.873800,706.873800
XS GIS Cut Line= 6
1199867.50173241616200.891097203 1198662.1277957616815.874824479
1198569.42426145616820.4678738561198531.52041534616825.723583743
1198417.68488494616855.0354489681198159.22260544617239.760078855
#Sta/Elev= 30
8420.38968.114338472.19866.487828483.81367.955398538.49561.889098582.69362.26245
8601.10958.36309 8637.9455.409178726.33753.967558765.35648.193448855.24843.56104
 8881.0338.973638924.17541.201168969.42636.230279043.08938.500799238.29838.16847
9293.54541.98962 9404.0436.911779643.44736.648839815.49432.742129874.41434.97002
 9934.3732.635089971.73727.977419988.77728.2035110005.82 24.6905 10022.332.37722
 10040.936.5345210095.0439.5971110152.6838.2387910311.5341.4007610485.7939.13623
#Mann= 3 , 0 , 0
8420.389    0.12       08420.389    0.12       010485.79    0.12       0
#XS Ineff= 2 , 0
       09864.132        10120.88       0
Bank Sta=8420.389,10485.79
Exp/Cntr=0.3,0.1

Type RM Length L Ch R = 1 ,1520.873,510.786200,510.786200,510.786200
XS GIS Cut Line= 6
1199830.30700108615731.7582023291199330.47498181616000.438971594
 1198464.7032727616287.6093007481198287.04507881616411.467651099
1198202.02635455616623.8902622161197906.36498239617147.811852288
#Sta/Elev= 30
  8740.270.654918776.44162.501648800.74759.702648854.51858.288548900.04954.41499
9061.02350.213099102.00946.703599284.15943.390819560.93330.464449648.24828.93989
9669.07426.21486  9689.9 27.56619766.26324.92991 9859.7126.472849962.85623.91707
9973.05823.142769986.68117.5718710010.54 18.3234 10037.824.1216210054.8425.45437
 10109.222.9545710258.2523.2790910343.7524.3811210363.7526.05906 10482.926.29026
10521.7729.2250810546.5127.5362310757.04 32.143110964.2430.2738111268.7634.20506
#Mann= 3 , 0 , 0
  8740.2  0.0771       0  8740.2  0.0771       011268.76  0.0771       0
#XS Ineff= 2 , 0
       09837.143         10108.6       0
Bank Sta=8740.2,11268.76
Exp/Cntr=0.3,0.1

Type RM Length L Ch R = 1 ,1010.087,546.502300,546.502300,546.502300
XS GIS Cut Line= 6
 1199383.3508085614882.1403851511198734.05234501615551.602993563
1198364.11295608615850.8536413911198242.88583872616010.637625754
1198147.58078378616452.6163478341197792.37547916617106.361123835
#Sta/Elev= 30
8708.75338.313928863.43927.05685  9060.626.001919087.84622.79425 9110.55 24.2309
9219.59520.570479248.36621.616459392.77916.14587 9598.7216.180649635.41818.92607
 9664.4717.048759741.825 19.60989752.22817.634519810.89316.618879952.10819.26204
 9997.53 12.505810036.8518.5430810165.8120.66842 10202.217.3962810502.5319.23144
10698.2723.7064110815.2229.99969 10878.728.1393110953.37 29.386211016.8527.26156
11095.2628.6592911199.8127.3755911367.83 30.013811418.7532.8417811517.9431.49779
#Mann= 3 , 0 , 0
8708.753    0.12       08708.753    0.12       011517.94    0.12       0
#XS Ineff= 2 , 0
       0 9939.47        10040.03       0
Bank Sta=8708.753,11517.94
Exp/Cntr=0.3,0.1