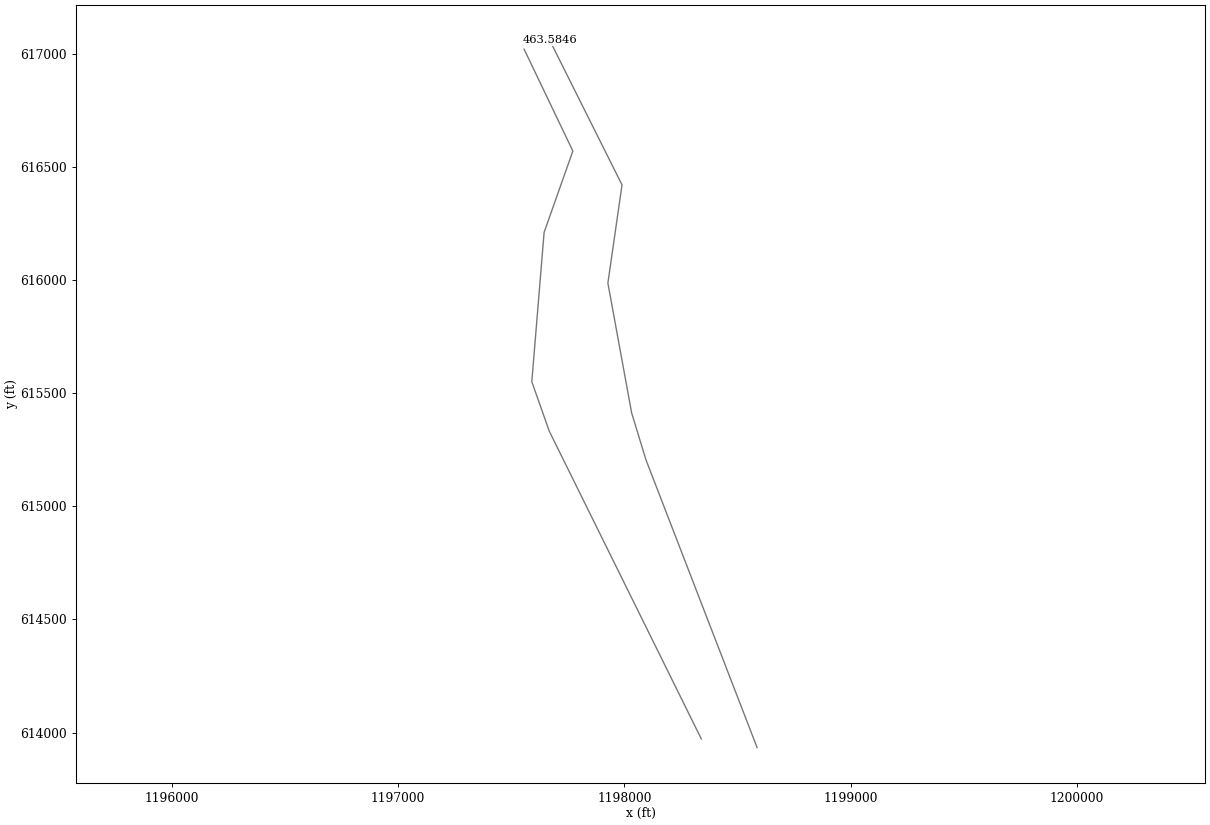
HEC-RAS study 148_ras.prj: 148

--- 148_ras.g01 (geometry) --- (continued)

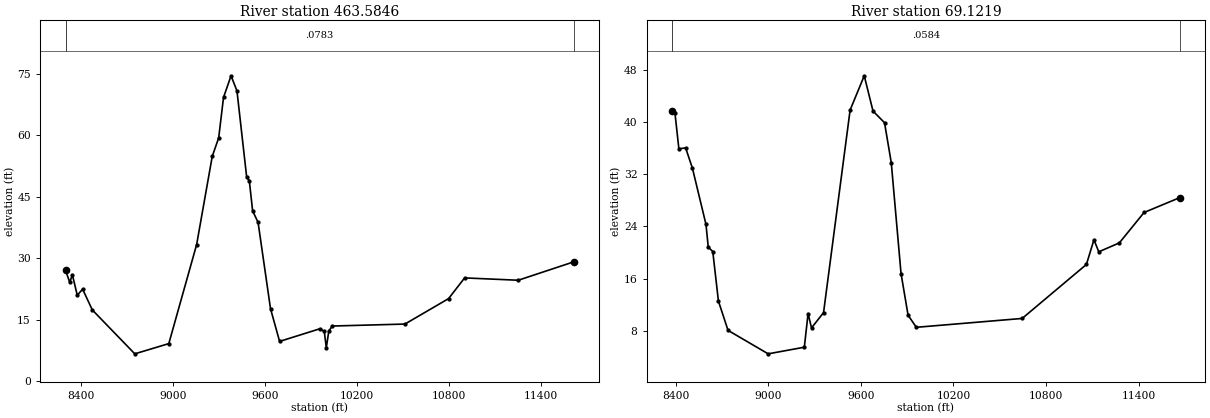
Type RM Length L Ch R = 1 ,463.5846,394.462700,394.462700,394.462700
XS GIS Cut Line= 6
1198586.49220714 613933.670134471198095.37870061615205.337131277
1198032.17062241 615411.989158721197926.97742891615986.859573394
1197989.42004734616420.9844440221197669.06281354617061.520154516
#Sta/Elev= 30
8296.59327.059648324.12524.138168341.69225.942318373.31420.967198408.44922.44318
8471.69317.370588749.2616.6412518971.4739.1406569153.31533.342389255.20754.88094
 9297.3759.422369329.01869.318539378.18174.589749416.82970.885519480.07349.86867
9497.67148.870789519.06541.59046 9554.7238.764979635.97717.674019695.3039.679148
9957.21712.752919987.18112.1479410000.478.12781410017.0912.2680710040.3713.43632
10514.1413.91763 10799.2  20.13410904.22 25.197311254.3524.6263611615.8129.10351
#Mann= 3 , 0 , 0
8296.593  0.0783       08296.593  0.0783       011615.81  0.0783       0
#XS Ineff= 2 , 0
       09417.059        10166.59       0
Bank Sta=8296.593,11615.81
Exp/Cntr=0.3,0.1

Type RM Length L Ch R = 1 , 69.1219,0.000000,0.000000,0.000000
XS GIS Cut Line= 6
1198339.96442941613971.8645789031197667.83282977615332.403761506
1197590.66217193615551.0189664071197645.03766531616211.052638412
1197772.10151207616570.5503510091197556.66677701617020.648868502
#Sta/Elev= 30
  8376.441.630688395.423 41.44518421.05935.910858465.00736.035638508.95532.92248
8596.85124.305698611.50120.823228640.79920.152528677.42312.553788739.6838.064368
8999.7094.4663239234.0985.4823959258.42110.648569280.569 8.442949358.61810.78724
9530.74841.842579622.30647.09747 9679.2841.680799753.71739.904589797.41833.77296
9860.70216.782339906.40310.383649959.8428.53488110645.649.89206211062.0418.17217
11110.7521.9562311142.07 20.109411275.4121.4770811435.4526.1359911668.5128.43175
#Mann= 3 , 0 , 0
  8376.4  0.0584       0  8376.4  0.0584       011668.51  0.0584       0
#XS Ineff= 2 , 0
       0 9615.61        10332.22       0
Bank Sta=8376.4,11668.51
Exp/Cntr=0.3,0.1